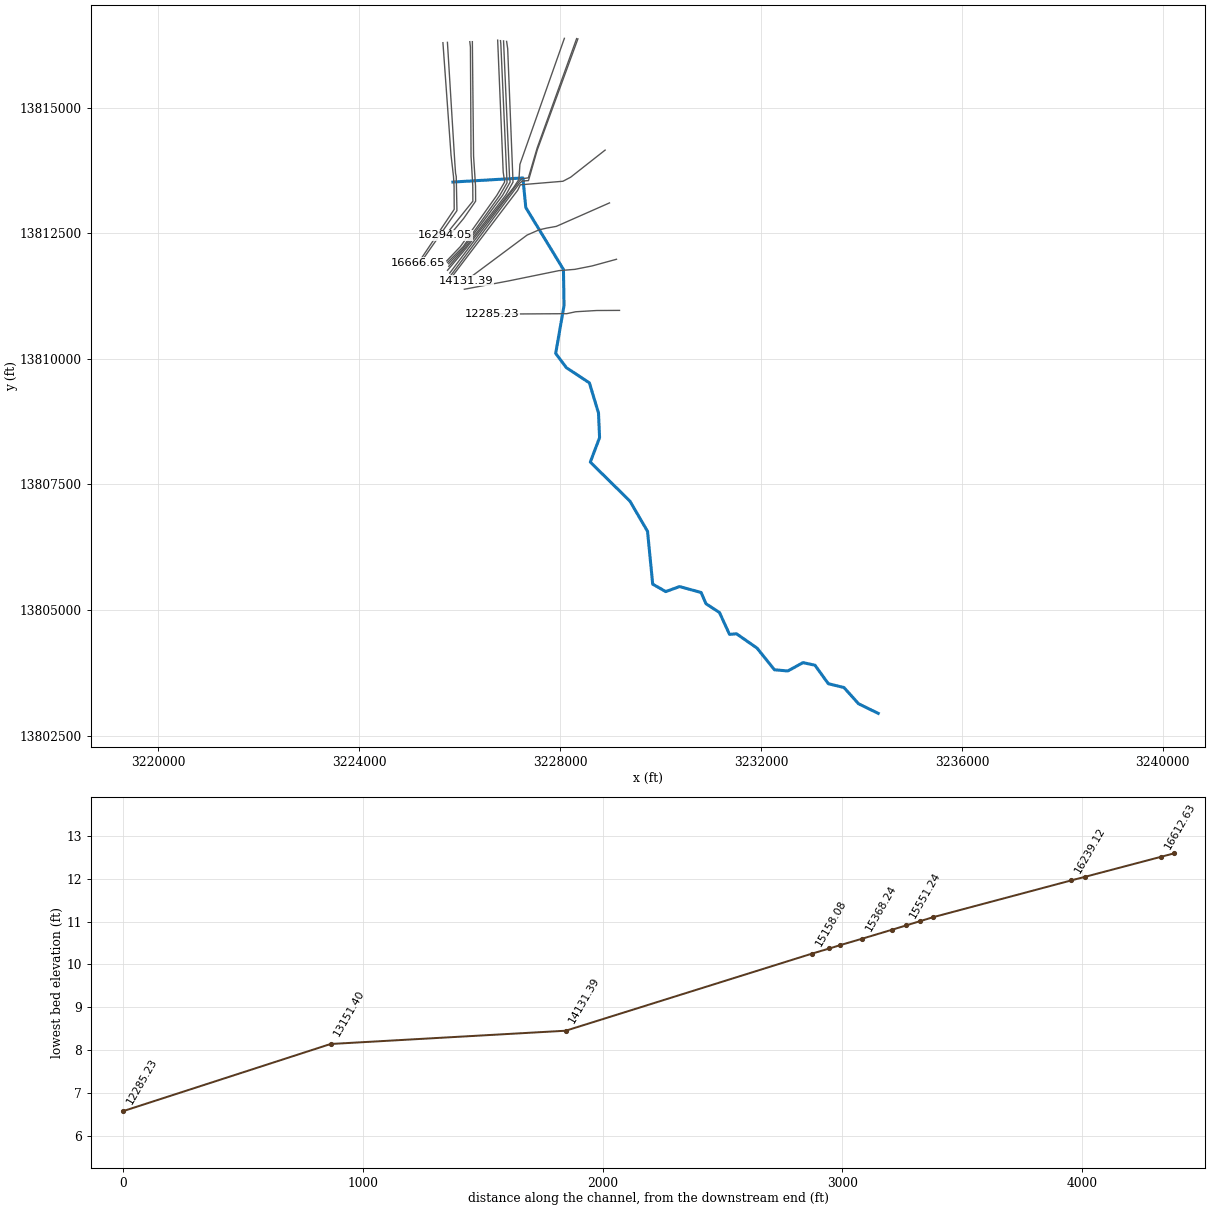
--- F216-00-00.prj (project) ---

Proj Title=F216-00-00
Current Plan=p06
Default Exp/Contr=.3,.1
English Units
Geom File=g03
Flow File=f01
Flow File=f02
Plan File=p05
Plan File=p06
Y Axis Title=Elevation
X Axis Title(PF)=Main Channel Distance
X Axis Title(XS)=Station
BEGIN DESCRIPTION:
Galveston Bay Watershed
Little Cedar Bayou
HCFCD unit F216-00-00
(Flood Hazard, Floodway)Model
10, 2, 1, 0.2% Event
Filename F2160000.prj
Prepared by:  FTN Associates Ltd.   DATE:  February 2003
Reviewed by:     DATE:
STATUS (Final)
Starting condition is normal depth, channel slope = 0.000336 computed from RS 538.67 (471v1) @ -4.36 ft and RS 1936.48 (471s1d) @ -3.89 ft.  Compares to Previous FIS starting condition of 0.000834.
Flow Paths have been adjusted to be within the 100yr flow.
END DESCRIPTION:
DSS Export Rating Curves= 0
DSS Export Rating Curve Sorted= 0
DSS Export Volume Flow Curves= 0
DXF Filename=R:\hh\2290-111\litcdrbay-47\LittleCedarBayou-471\hyls\471-ras\water surface.dxf
DXF OffsetX= 0
DXF OffsetY= 0
DXF ScaleX= 1
DXF ScaleY= 10

--- F216-00-00.p06 (plan) ---

Plan Title=Floodway
Version=Version 3.0.1  Mar 2001
Short Identifier=Floodway0607
Geom File=g03
Flow File=f02
Subcritical Flow
K Sum by GR= 0
Std Step Tol= 0.01
Critical Tol= 0.01
Num of Std Step Trials= 20
Max Error Tol= 0.3
Flow Tol Ratio= 0.001
Split Flow NTrial= 30
Split Flow Tol= 0.02
Split Flow Ratio= 0.02
Log Output Level= 0
Friction Slope Method= 1
Unsteady Friction Slope Method= 2
Parabolic Critical Depth
Global Vel Dist= 0 , 0 , 0
Global Log Level= 0
CheckData=True
Encroach Param=-1 ,0,0, 2
Encroach River=F216-00-00
Encroach Reach=Little Cedar
Encroach Node=16666.65
       1    2698 2810.06
Encroach Node=16612.63
       1    2696 2814.11
Encroach Node=16453.34
       1    2621 2814.11
Encroach Node=16294.05
       1    2621 2803.79
Encroach Node=16239.12
       1    2623 2802.91
Encroach Node=15662.67
       1    2502    3213
Encroach Node=15609.67
       1    2443    3249
Encroach Node=15580.45
       1    2392    3291
Encroach Node=15551.24
       1    2392    3291
Encroach Node=15493.04
       1    2325    3339
Encroach Node=15368.24
       1    2260    3625
Encroach Node=15276.72
       1    2417    3815
Encroach Node=15253.54
       1    2417    3815
Encroach Node=15230.36
       1    2450    3810
Encroach Node=15158.08
       1    1467    2620
Encroach Node=14131.39
       1    1196    1700
Encroach Node=13151.40
       1     780     980
Encroach Node=12285.23
       1  887.85    1045
Encroach Node=12213.19
       1  887.85    1006
Encroach Node=12138.43
       1  887.85    1006
Encroach Node=12063.67
       1  887.85    1006
Encroach Node=11962.65
       1    1050    1176
Encroach Node=11103.33
       1  1037.9    1210
Encroach Node=10051.04
       1  681.27  795.87
Encroach Node=8905.061
       1    1186    1300
Encroach Node=8551.573
       1    1230 1347.45
Encroach Node=8249.000
       1    1208 1321.79
Encroach Node=8208.269
       1 1081.98 1263.56
Encroach Node=7970.648
       1 1077.12 1263.56
Encroach Node=7733.031
       1 1077.12  1258.7
Encroach Node=7679.985
       1 1676.53    1861
Encroach Node=7404.070
       1    1728  1970.5
Encroach Node=7222.301
       1  1283.5    1460
Encroach Node=6759.369
       1    1781  1965.5
Encroach Node=6699.486
       1    1860 2023.15
Encroach Node=6659.565
       1    1940 2081.38
Encroach Node=6602.855
       1    1940 2101.36
Encroach Node=6546.143
       1    1940 2101.36
Encroach Node=6500.687
       1 2256.48 2373.55
Encroach Node=6445.129
       1 2310.14 2429.04
Encroach Node=5777.244
       1 2593.37 2723.75
Encroach Node=5733.993
       1 2642.42  2771.9
Encroach Node=5699.263
       1    2622 2773.53
Encroach Node=5664.537
       1    2622 2773.53
Encroach Node=5615.555
       1    2595 2771.31
Encroach Node=5380.519
       1    2382 2580.22
Encroach Node=5255.402
       1  2108.5 2286.17
Encroach Node=4475.840
       1    1160 1264.94
Encroach Node=3384.195
       1  817.31  921.01
Encroach Node=2707.204
       1   580.5  691.54
Encroach Node=2123.560
       1  548.78  702.24
Encroach Node=2021.986
       1  524.57  678.03
Encroach Node=1979.236
       1  524.57  678.03
Encroach Node=1936.482
       1  516.98  670.44
Encroach Node=1834.600
       1  503.69  657.15
Encroach Node=1452.611
       1  872.92 1043.42
Encroach Node=538.677
       1  1204.7 1415.04
Encroach Reach=F216-00-00_0005
Encroach Node=16666.65
       1    2698 2810.06
Encroach Node=16612.63
       1    2696 2814.11
Encroach Node=16453.34
       1    2621 2814.11
Encroach Node=16294.05
       1    2621 2803.79
Encroach Node=16239.12
       1    2623 2802.91
Encroach Node=15662.67
       1    2502    3213
Encroach Node=15609.67
       1    2443    3249
Encroach Node=15580.45
       1    2392    3291
Encroach Node=15551.24
       1    2392    3291
Encroach Node=15493.04
       1    2325    3339
Encroach Node=15368.24
       1    2260    3625
Encroach Node=15276.72
       1    2417    3815
Encroach Node=15253.54
       1    2417    3815
Encroach Node=15230.36
       1    2450    3810
Encroach Node=15158.08
       1    1467    2620
Encroach Node=14131.39
       1    1196    1700
Encroach Node=13151.40
       1     780     980
Encroach Node=12285.23
       1  887.85    1045
Encroach Node=12213.19
       1  887.85    1006
Encroach Node=12138.43
       1  887.85    1006
Encroach Node=12063.67
       1  887.85    1006
Encroach Node=11962.65
       1    1050    1176
Encroach Node=11103.33
       1  1037.9    1210
Encroach Node=10051.04
       1  681.27  795.87
Encroach Node=8905.061
       1    1186    1300
Encroach Node=8551.573
       1    1230 1347.45
Encroach Node=8249.000
       1    1208 1321.79
Encroach Node=8208.269
       1 1081.98 1263.56
Encroach Node=7970.648
       1 1077.12 1263.56
Encroach Node=7733.031
       1 1077.12  1258.7
Encroach Node=7679.985
       1 1676.53    1861
Encroach Node=7404.070
       1    1728  1970.5
Encroach Node=7222.301
       1  1283.5    1460
Encroach Node=6759.369
       1    1781  1965.5
Encroach Node=6699.486
       1    1860 2023.15
Encroach Node=6659.565
       1    1940 2081.38
Encroach Node=6602.855
       1    1940 2101.36
Encroach Node=6546.143
       1    1940 2101.36
Encroach Node=6500.687
       1 2256.48 2373.55
Encroach Node=6445.129
       1 2310.14 2429.04
Encroach Node=5777.244
       1 2593.37 2723.75
Encroach Node=5733.993
       1 2642.42  2771.9
Encroach Node=5699.263
       1    2622 2773.53
Encroach Node=5664.537
       1    2622 2773.53
Encroach Node=5615.555
       1    2595 2771.31
Encroach Node=5380.519
       1    2382 2580.22
Encroach Node=5255.402
       1  2108.5 2286.17
Encroach Node=4475.840
       1    1160 1264.94
Encroach Node=3384.195
       1  817.31  921.01
Encroach Node=2707.204
       1   580.5  691.54
Encroach Node=2123.560
       1  548.78  702.24
Encroach Node=2021.986
       1  524.57  678.03
Encroach Node=1979.236
       1  524.57  678.03
Encroach Node=1936.482
       1  516.98  670.44
Encroach Node=1834.600
       1  503.69  657.15
Encroach Node=1452.611
       1  872.92 1043.42
Encroach Node=538.677
       1  1204.7 1415.04
Computation Interval=1HOUR
Output Interval=1HOUR
Run HTab= 0
Run UNet= 0
Run PostProcess= 0
UNET Theta= 1
UNET ZTol= 0.02
UNET ZSATol= 0.1
UNET MxIter= 20
UNET MaxInSteps= 20
UNET DtIC= 0
UNET DtMin= 0
UNET MaxCRTS= 20
UNET WFStab= 2
UNET SFStab= 1
UNET WFX= 1
UNET SFX= 1
UNET Convert EG Bridges=-1
UNET Use Existing IB Tables=-1
Instantaneous Interval=1HOUR
Write IC File= 0
Write Velocity= 0
Write Detailed= 0

--- F216-00-00.p05 (plan) ---

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Plan Title=FEMA Effective June 2007
Short Identifier=FEMAeff0607
Geom File=g03
Flow File=f01
Encroach Param=-1 ,0,0, 0
IC Time=0

--- F216-00-00.f02 (steady flow) ---

Flow Title=Floodway
Version=Version 3.0.1  Mar 2001
Number of Profiles= 2
Profile Names=1PCT_100yr, 1PCTFloodway_100yrFW
River Rch & RM=F216-00-00,F216-00-00_0005    ,16666.65
     541     541
River Rch & RM=F216-00-00,F216-00-00_0005    ,16612.63
     566     566
River Rch & RM=F216-00-00,F216-00-00_0005    ,16294.05
     571     571
River Rch & RM=F216-00-00,F216-00-00_0005    ,16239.12
     619     619
River Rch & RM=F216-00-00,F216-00-00_0005    ,15662.67
     623     623
River Rch & RM=F216-00-00,F216-00-00_0005    ,15609.67
     653     653
River Rch & RM=F216-00-00,F216-00-00_0005    ,15276.72
     664     664
River Rch & RM=F216-00-00,F216-00-00_0005    ,15158.08
     767     767
River Rch & RM=F216-00-00,F216-00-00_0005    ,14131.39
     880     880
River Rch & RM=F216-00-00,F216-00-00_0005    ,13151.40
     994     994
River Rch & RM=F216-00-00,F216-00-00_0005    ,12285.23
    1004    1004
River Rch & RM=F216-00-00,F216-00-00_0005    ,12213.19
    1021    1021
River Rch & RM=F216-00-00,F216-00-00_0005    ,11962.65
    1082    1082
River Rch & RM=F216-00-00,F216-00-00_0005    ,11103.33
    1162    1162
River Rch & RM=F216-00-00,F216-00-00_0005    ,10051.04
    1256    1256
River Rch & RM=F216-00-00,F216-00-00_0005    ,8905.061
    1317    1317
River Rch & RM=F216-00-00,F216-00-00_0005    ,8208.269
    1360    1360
River Rch & RM=F216-00-00,F216-00-00_0005    ,7733.031
    1408    1408
River Rch & RM=F216-00-00,F216-00-00_0005    ,7222.301
    1484    1484
River Rch & RM=F216-00-00,F216-00-00_0005    ,6445.129
    1553    1553
River Rch & RM=F216-00-00,F216-00-00_0005    ,5777.244
    1609    1609
River Rch & RM=F216-00-00,F216-00-00_0005    ,5255.402
    1696    1696
River Rch & RM=F216-00-00,F216-00-00_0005    ,4475.840
    1826    1826
River Rch & RM=F216-00-00,F216-00-00_0005    ,3384.195
    1912    1912
River Rch & RM=F216-00-00,F216-00-00_0005    ,2707.204
    1989    1989
River Rch & RM=F216-00-00,F216-00-00_0005    ,2123.560
    2082    2082
River Rch & RM=F216-00-00,F216-00-00_0005    ,1452.611
    2799    2799
Boundary for River Rch & Prof#=F216-00-00,F216-00-00_0005    , 1
Up Type= 0
Dn Type= 3
Dn Slope=.000336
DSS Import GetInterval= 0
DSS Import GetPeak= 0
DSS Import FillOption= 0

--- F216-00-00.f01 (steady flow) ---

Flow Title=FEMA Effective June 2007
Version=Version 3.0.1  Mar 2001
Number of Profiles= 4
Profile Names=10PCT_10yr, 2PCT_50yr, 1PCT_100yr, 0.2PCT_500yr
River Rch & RM=F216-00-00,F216-00-00_0005    ,16666.65
     307     461     541     779
River Rch & RM=F216-00-00,F216-00-00_0005    ,16612.63
     321     482     566     815
River Rch & RM=F216-00-00,F216-00-00_0005    ,16294.05
     324     486     571     821
River Rch & RM=F216-00-00,F216-00-00_0005    ,16239.12
     351     527     619     890
River Rch & RM=F216-00-00,F216-00-00_0005    ,15662.67
     354     531     623     897
River Rch & RM=F216-00-00,F216-00-00_0005    ,15609.67
     371     556     653     940
River Rch & RM=F216-00-00,F216-00-00_0005    ,15276.72
     377     566     664     956
River Rch & RM=F216-00-00,F216-00-00_0005    ,15158.08
     435     653     767    1104
River Rch & RM=F216-00-00,F216-00-00_0005    ,14131.39
     500     750     880    1266
River Rch & RM=F216-00-00,F216-00-00_0005    ,13151.40
     564     847     994    1430
River Rch & RM=F216-00-00,F216-00-00_0005    ,12285.23
     570     855    1004    1445
River Rch & RM=F216-00-00,F216-00-00_0005    ,12213.19
     580     871    1021    1468
River Rch & RM=F216-00-00,F216-00-00_0005    ,11962.65
     617     925    1082    1551
River Rch & RM=F216-00-00,F216-00-00_0005    ,11103.33
     666     997    1162    1660
River Rch & RM=F216-00-00,F216-00-00_0005    ,10051.04
     723    1081    1256    1787
River Rch & RM=F216-00-00,F216-00-00_0005    ,8905.061
     760    1135    1317    1869
River Rch & RM=F216-00-00,F216-00-00_0005    ,8208.269
     786    1174    1360    1927
River Rch & RM=F216-00-00,F216-00-00_0005    ,7733.031
     816    1217    1408    1991
River Rch & RM=F216-00-00,F216-00-00_0005    ,7222.301
     863    1286    1484    2093
River Rch & RM=F216-00-00,F216-00-00_0005    ,6445.129
     905    1349    1553    2185
River Rch & RM=F216-00-00,F216-00-00_0005    ,5777.244
     940    1399    1609    2259
River Rch & RM=F216-00-00,F216-00-00_0005    ,5255.402
     994    1479    1696    2375
River Rch & RM=F216-00-00,F216-00-00_0005    ,4475.840
    1075    1597    1826    2548
River Rch & RM=F216-00-00,F216-00-00_0005    ,3384.195
    1129    1676    1912    2661
River Rch & RM=F216-00-00,F216-00-00_0005    ,2707.204
    1177    1746    1989    2763
River Rch & RM=F216-00-00,F216-00-00_0005    ,2123.560
    1236    1831    2082    2884
River Rch & RM=F216-00-00,F216-00-00_0005    ,1452.611
    1649    2440    2799    3842
Boundary for River Rch & Prof#=F216-00-00,F216-00-00_0005    , 1
Up Type= 0
Dn Type= 3
Dn Slope=.000336
DSS Import GetInterval= 0
DSS Import GetPeak= 0
DSS Import FillOption= 0

--- F216-00-00.g03 (geometry) ---

Geom Title=F216-00-00 June 2007
Version=Version 3.0.1  Mar 2001

River Reach=F216-00-00      ,F216-00-00_0005
Reach XY= 30
     3225868.434    13813519.121     3227261.394    13813600.704
     3227318.804    13813011.491     3228068.162    13811778.677
     3228080.248    13811062.556      3227914.06    13810107.729
     3228125.369     13809824.95     3228584.856    13809521.538
     3228766.152    13808920.239     3228787.304    13808430.739
     3228602.986    13807944.261     3229391.625    13807167.708
     3229742.131    13806566.409     3229844.865    13805514.891
     3230104.723    13805366.832     3230379.689    13805466.545
     3230808.757    13805348.703     3230905.448    13805125.104
     3231174.371    13804949.851     3231373.797     13804514.74
     3231512.791    13804526.826     3231920.707    13804242.795
     3232268.192    13803810.706     3232534.093    13803786.533
     3232836.253    13803952.721      3233074.96    13803901.354
     3233340.861    13803532.718     3233652.087    13803457.178
     3233942.161    13803133.867     3234334.811    13802942.465

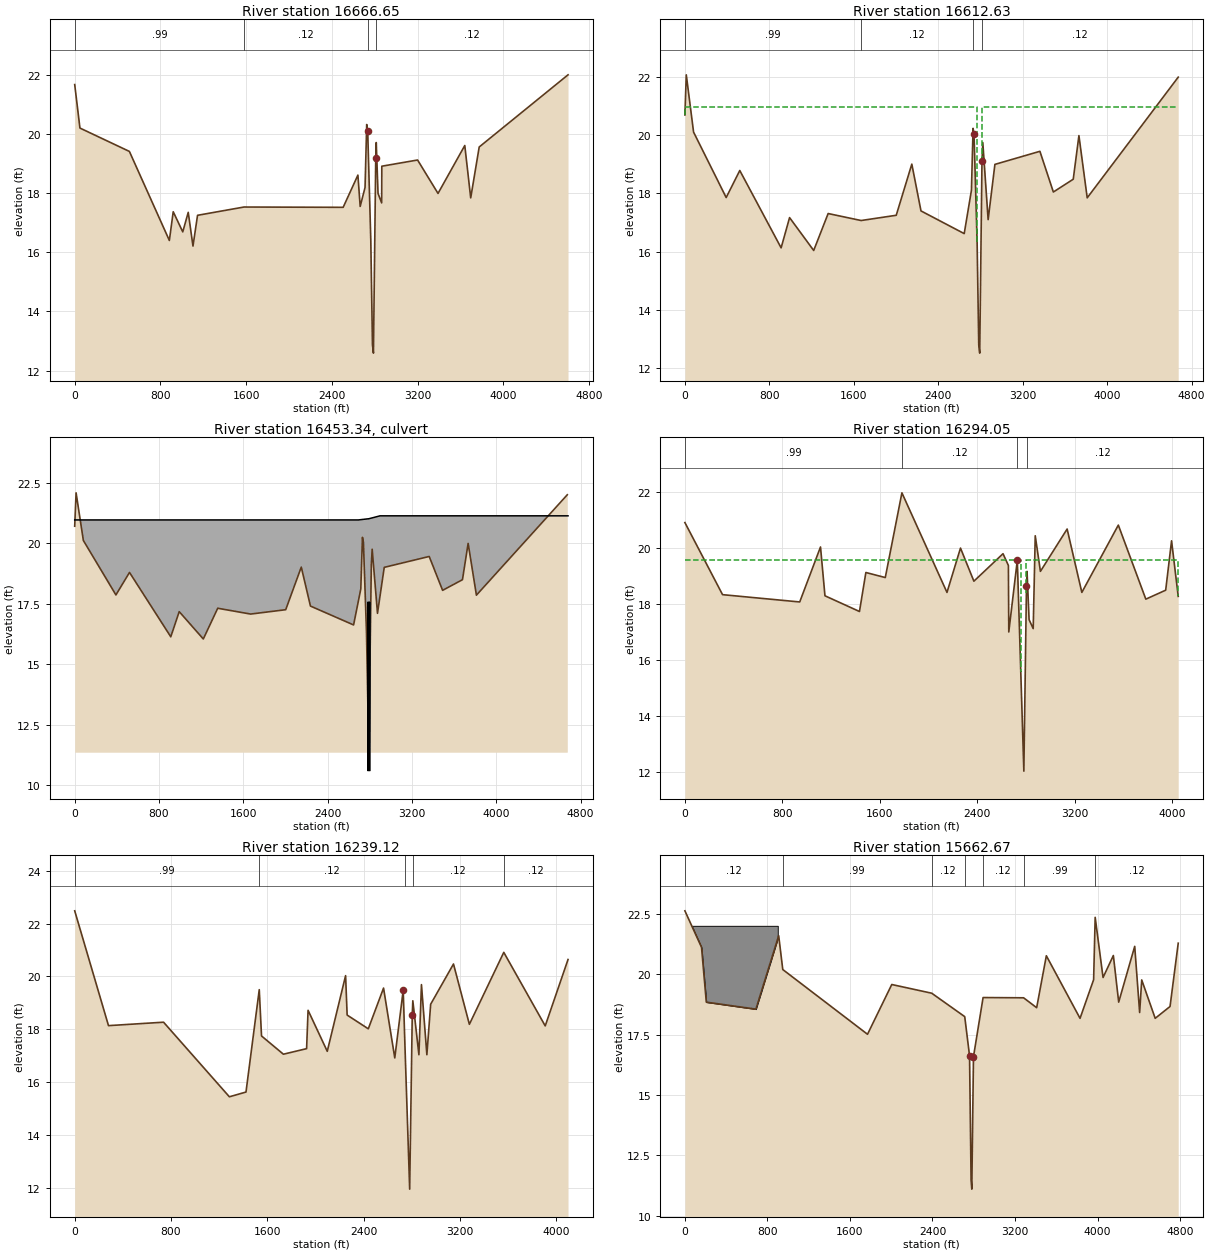
Type RM Length L Ch R = 1 ,16666.65,58.7,54.01,53.83
BEGIN DESCRIPTION:
471s12u:  XS 4/4
Bank Station offset =      2211
XS extended on ROB
END DESCRIPTION:
XS GIS Cut Line= 6
     3225669.267    13816292.918     3225830.619    13814055.468
     3225879.489    13813630.436     3225891.152    13813435.532
     3225893.673    13812974.805 3225182.042033613811913.8412869
#Sta/Elev= 30
       0   21.67   48.85    20.2   510.5   19.41  883.55    16.4  919.62   17.37
 1008.63   16.69 1059.78   17.35 1104.08   16.21 1146.65   17.25 1580.21   17.53
 2505.98   17.52 2643.57   18.61 2664.88   17.55 2710.18   18.19 2725.67   20.32
 2734.88   20.11 2763.96    16.4 2779.46   12.87 2788.59   12.59 2810.06   19.19
 2814.75   19.71  2831.5   17.99  2865.3   17.67 2866.73   18.91 3200.64   19.12
 3391.42   17.99 3641.25   19.61 3696.62   17.84  3775.9   19.56    4605      22
#Mann= 4 ,-1 , 0
       0     .99       0 1580.21     .12       0 2734.88    .045       0
 2814.75     .12       0
Bank Sta=2734.88,2810.06
XS Rating Curve= 0
Exp/Cntr=.5,.3

Type RM Length L Ch R = 1 ,16612.63,325.94,318.58,319.07
BEGIN DESCRIPTION:
Copy of 471s12 u.  XS 3/4.
Bank Station offset =      2207
XS extended on ROB
END DESCRIPTION:
XS GIS Cut Line= 6
     3225758.871    13816299.811     3225904.903    13813921.925
     3225920.771    13813693.145     3225934.489    13813630.436
     3225948.395    13812950.133 3225194.135602913811871.1258256
#Sta/Elev= 30
       0    20.7   13.09   22.08   82.16   20.11  391.04   17.86  519.86   18.79
  911.43   16.13  991.51   17.17 1220.04   16.04 1356.88   17.31 1669.24   17.07
 2001.78   17.25 2149.51   19.01 2236.37    17.4 2645.78   16.62 2714.23   18.11
 2729.72   20.24 2738.93   20.03 2768.01   16.32 2783.51   12.79 2792.64   12.51
 2814.11   19.11  2821.9   19.75 2872.44    17.1 2936.53      19 3362.84   19.45
 3490.21   18.05 3678.61   18.49 3732.37   19.99 3810.92   17.85    4673      22
#Mann= 4 ,-1 , 0
       0     .99       0 1669.24     .12       0 2729.72    .045       0
 2814.11     .12       0
#XS Ineff= 2 , 0
       0    2768   20.96    2814       0   20.96
Permanent Ineff=
       F       F
Bank Sta=2738.93,2814.11
XS Rating Curve= 0
Exp/Cntr=.5,.3

Type RM Length L Ch R = 2 ,16453.34,,,
BEGIN DESCRIPTION:
SPTC RR  (Strang Yard), 471s12, elliptical culvert
Assumed width of deck based on photos.
Using concrete ellipse but actually is CMP, entrance loss reflects CMP.
Top of deck/roadway extensions assumed based on aerial photos and GIS tin elevations.
END DESCRIPTION:
Bridge Culvert--1,0,-1,-1, 0
Deck Dist Width WeirC Skew NumUp NumDn MinLoCord MaxHiCord MaxSubmerge Is_Ogee
16.7,285,2.6,0, 7, 7, 20.96, , .95, 0, 0,0,,
       0    2643 2690.19    2791 2896.82    3360    4680
   20.96   20.96   20.96   21.01   21.13   21.13   21.13
       0       0       0       0       0       0
       0    2632 2679.19    2780 2885.82    3619 4049.48
   20.96   20.96   20.96   21.01   21.13   21.13   21.13
       0       0       0       0       0       0
BR Coef=-1 , 0 , 0 ,, 0 ,,,.8,0,,0,
WSPro=,,,, 1 ,,,, 0 ,,,, 0 ,,,,-1 ,-1 ,-1 , 0 , 0 , 0 , 0 , 0
Multiple Barrel Culv=4,7,9,299,.024,.7,1,29,3,10.58,10.87, 2,Culvert #1  , 0 ,10
    2784    2773    2798    2787
Culvert Bottom n=.024
BC Design=,, 0 ,, 0 ,,,,,,

Type RM Length L Ch R = 1 ,16294.05,52.75,54.93,54.93
BEGIN DESCRIPTION:
Copy of 471s12 u.  XS 2/4. .
Bank Station offset =      2218
END DESCRIPTION:
XS GIS Cut Line= 6
     3226204.415     13816313.52     3226216.617    13816203.998
     3226229.019    13814034.306     3226263.287    13813440.351
     3226265.247    13813138.565     3225718.398    13812459.578
#Sta/Elev= 30
       0    20.9  309.03   18.33  942.47   18.07 1113.17   20.03 1149.73   18.29
 1432.88   17.73 1485.52   19.12 1644.83   18.94 1781.36   21.96 2151.35   18.41
 2262.28   19.99 2372.22   18.81 2611.25   19.79 2655.47   19.37 2658.61      17
 2728.61   19.56 2782.32   12.04 2803.79   18.64 2808.48   19.16 2825.23   17.44
 2859.03   17.12 2875.79   20.43 2918.28   19.16 3137.54   20.67 3258.34   18.41
 3557.84   20.81 3783.52   18.17 3946.58   18.49 3994.79   20.25 4049.48   18.27
#Mann= 4 ,-1 , 0
       0     .99       0 1781.36     .12       0 2728.61    .045       0
 2808.48     .12       0
#XS Ineff= 2 , 0
       0    2757   19.55    2803       0   19.55
Permanent Ineff=
       F       F
#Block Obstruct= 2 , 0
       0                 3977.35       0   20.31
Bank Sta=2728.61,2803.79
XS Rating Curve= 0
Exp/Cntr=.5,.3

Type RM Length L Ch R = 1 ,16239.12,579.76,576.45,524.42
BEGIN DESCRIPTION:
Copy of 471s12 u.  XS 1/4.
Bank Station offset =      2219
END DESCRIPTION:
XS GIS Cut Line= 6
     3226255.287     13816313.52     3226279.235    13814034.329
     3226318.287    13813440.351     3226320.247    13813138.565
     3226081.266    13812793.494     3225761.865    13812409.902
#Sta/Elev= 30
       0   22.48   280.6   18.14  737.85   18.27 1284.41   15.45 1422.31   15.63
 1532.44    19.5 1551.26   17.75 1732.91   17.06 1925.59   17.27 1937.73   18.72
 2097.13   17.17 2249.39   20.03 2262.13   18.54 2437.83   18.02  2564.5   19.56
 2657.73   16.92 2727.73   19.48 2741.84   17.43 2781.44   11.96 2802.91   18.56
  2807.6   19.08 2858.15   17.04 2879.22   19.69 2924.22   17.04 2955.75   18.95
 3145.23   20.47 3277.14   18.19 3562.88   20.91 3906.92   18.13 4096.31   20.64
#Mann= 5 ,-1 , 0
       0     .99       0 1532.44     .12       0 2741.84    .045       0
  2807.6     .12       0 3562.88     .12       0
Bank Sta=2727.73,2802.91
XS Rating Curve= 0
Exp/Cntr=.3,.1

Type RM Length L Ch R = 1 ,15662.67,63.5,52.99,52.72
BEGIN DESCRIPTION:
471s11u:   XS 4/4
Bank Station offset =      2219
Set special ineffective on LOB due to ineffective flow d/s of this bridge at high road (Barbours Cut Blvd, 471s10).
END DESCRIPTION:
XS GIS Cut Line= 6
     3226758.918    13816344.043     3226869.023    13813717.705
     3226897.931    13813519.825     3226742.422    13813254.437
     3226017.224    13812235.011     3225744.892    13811949.569
#Sta/Elev= 30
       0   22.62  161.05   21.11  207.54   18.84  688.37   18.55   909.2   21.59
  948.79   20.19 1770.21   17.51 2005.33   19.57 2392.48   19.21 2712.63   18.24
 2759.33   16.62 2774.26   11.48 2781.22    11.1 2797.43   16.58 2890.56   19.03
  3283.2   19.02 3409.93   18.61 3503.83   20.76 3830.42   18.17 3962.17   19.77
 3977.11   22.35 4053.56   19.86 4153.37   20.77 4205.13   18.84 4360.39   21.15
 4408.22   18.41 4428.32   19.76 4558.96   18.17 4702.89   18.66  4782.2   21.28
#Mann= 7 ,-1 , 0
       0     .12       0  948.79     .99       0 2392.48     .12       0
 2712.63    .045       0 2890.56     .12       0  3283.2     .99       0
 3977.11     .12       0
#Block Obstruct= 2 , 0
       0     900      22    4000       0      22
Bank Sta=2759.33,2797.43
XS Rating Curve= 0
Exp/Cntr=.5,.3

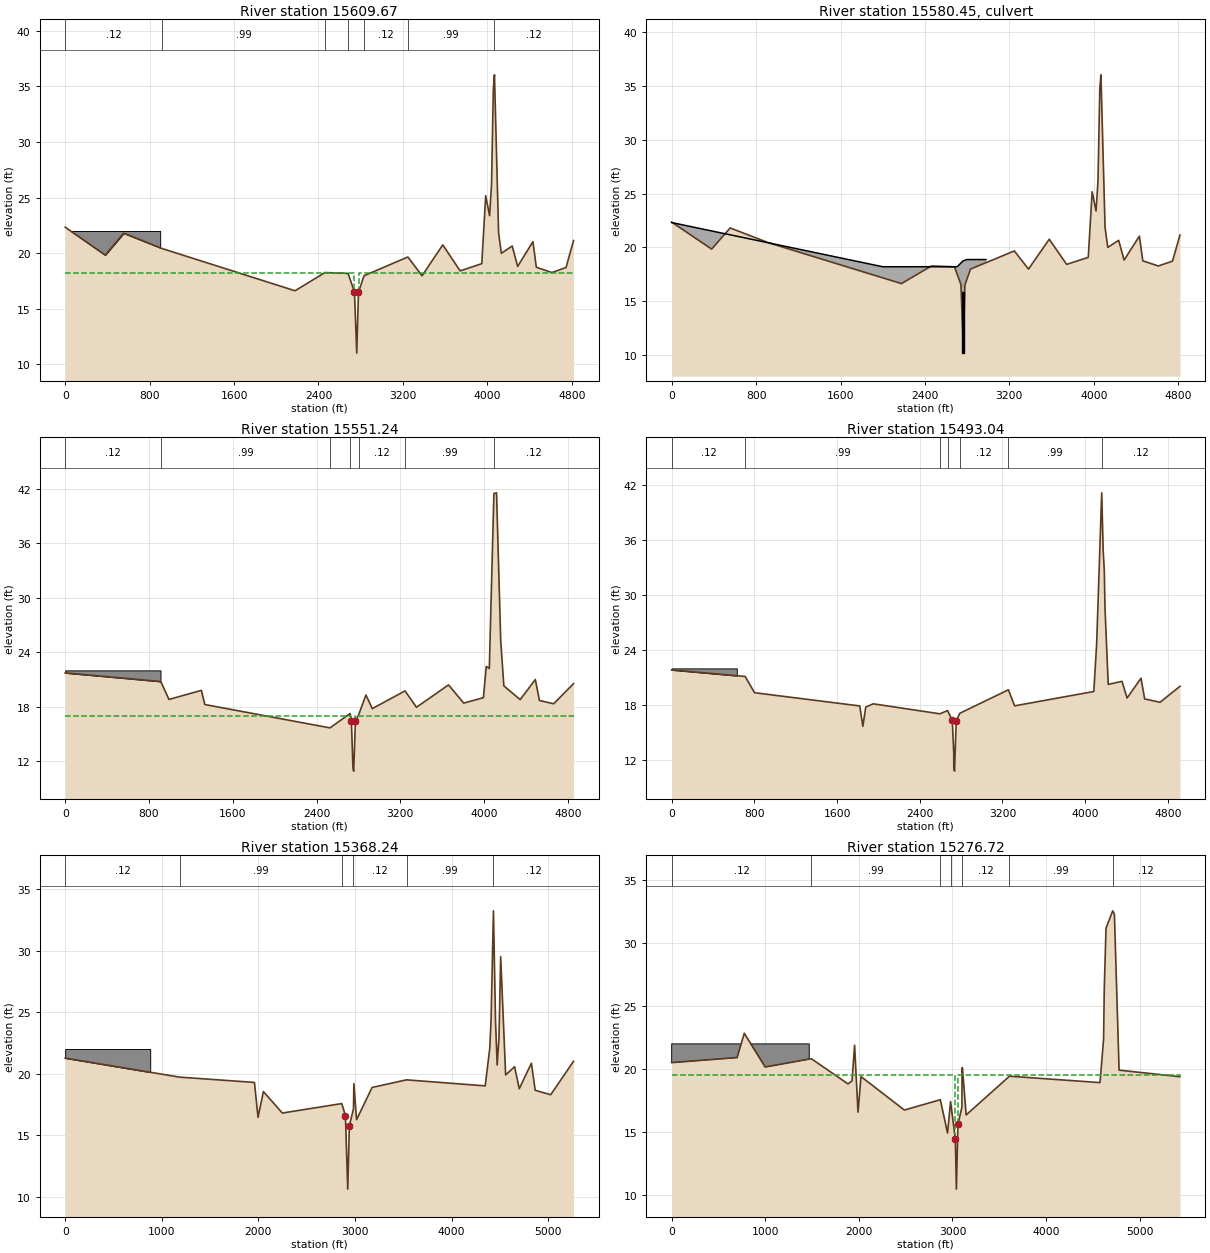
Type RM Length L Ch R = 1 ,15609.67,64.91,58.44,51.65
BEGIN DESCRIPTION:
Copy of 471s11 u.  XS 3/4.
Bank Station offset =      2237
Set special ineffective on LOB due to ineffective flow d/s of this bridge at high road (Barbours Cut Blvd, 471s10).
END DESCRIPTION:
XS GIS Cut Line= 6
     3226814.877    13816333.869      3226821.64    13816272.404
     3226945.526    13813505.198     3226801.422    13813254.437
     3226066.035    13812225.457     3225761.865     13811919.35
#Sta/Elev= 30
       0   22.34  379.25   19.83  554.34    21.8  918.52   20.42  2178.1   16.62
 2461.59   18.26 2680.49   18.18 2741.13   16.53 2763.02   11.01 2779.23   16.49
 2831.95   17.97 3247.39   19.66 3381.86   17.97 3578.25   20.75 3743.23   18.41
    3948   19.06 3984.87   25.17 4021.75   23.38 4040.18   26.15  4057.4   34.78
 4068.15   36.05 4107.28   21.84 4133.08   19.99 4236.27   20.65 4287.86   18.81
 4432.71   21.04 4464.77   18.74 4612.02   18.26 4746.29   18.71 4817.45   21.14
#Mann= 7 ,-1 , 0
       0     .12       0  918.52     .99       0 2461.59     .12       0
 2680.49    .045       0 2831.95     .12       0 3247.39     .99       0
 4068.15     .12       0
#XS Ineff= 2 , 0
       0 2739.75   18.19 2780.25       0   18.19
Permanent Ineff=
       F       F
#Block Obstruct= 2 , 0
       0     900      22    4020       0      22
Bank Sta=2741.13,2779.23
XS Rating Curve= 0
Exp/Cntr=.5,.3

Type RM Length L Ch R = 2 ,15580.45,,,
BEGIN DESCRIPTION:
(North) 16th St, 471s11, concrete box culvert.
Top of deck/roadway extensions assumed based on aerial photos and GIS tin elevations.
'Distance from upstream XS' of 5 being less than bridge opening of 5.7 is not considered to impact the model.  The cross sections are located outside the foot of the embankments.
END DESCRIPTION:
Bridge Culvert--1,0,-1,-1, 0
Deck Dist Width WeirC Skew NumUp NumDn MinLoCord MaxHiCord MaxSubmerge Is_Ogee
8.9,40.5,2.6,0, 7, 7, 18.19, , .95, 0, 0,0,,
       0    2000    2663 2705.55    2760 2795.33    2980
    22.3   18.19   18.19   18.19   18.72   18.86   18.86
       0       0       0       0       0       0       0
       0    2000    2655 2697.55    2752 2787.33    2870
    22.3   18.19   18.19   18.19   18.72   18.86   18.86
       0       0       0       0       0       0       0
BR Coef=-1 , 0 , 0 ,, 0 ,,,.8,0,,0,
WSPro=,,,, 1 ,,,, 0 ,,,, 0 ,,,,-1 ,-1 ,-1 , 0 , 0 , 0 , 0 , 0
Multiple Barrel Culv=2,5.7,10,40.5,.013,.5,1,10,1,10.15,10.12, 2,Culvert #1  , 0 ,5
 2754.75 2746.75 2765.25 2757.25
Culvert Bottom n=.013
BC Design=,, 0 ,, 0 ,,,,,,

Type RM Length L Ch R = 1 ,15551.24,46.26,58.2,55.91
BEGIN DESCRIPTION:
Copy of 471s11 u.  XS 2/4.
Bank Station offset =      2245
Set special ineffective on LOB as this will not effectively convey flow unless Barbours Cut Blvd just d/s is overtopped on LOB.(El. 19.6 to 20.0)
END DESCRIPTION:
XS GIS Cut Line= 6
     3226875.923    13816328.781     3226994.436    13813632.603
     3227006.728    13813518.798     3226857.422    13813254.437
     3226059.225    13812184.914     3225781.321     13811893.27
#Sta/Elev= 30
       0   21.72  913.05   20.77   991.1    18.8 1300.46    19.8 1333.47   18.24
 2528.79   15.67 2720.57   17.25  2733.2   16.43 2748.13   11.29 2755.09   10.91
  2771.3   16.39 2805.81   17.21 2872.02   19.29 2933.03   17.79 3245.46   19.74
 3354.68   17.94 3660.56    20.4 3806.09    18.4 3994.04   18.99 4021.37   22.43
 4050.28   22.21 4094.35   41.46 4119.43   41.54 4159.27   25.27 4189.31   20.29
 4345.15   18.78  4489.8   20.99 4529.02   18.69 4664.73   18.32  4854.7   20.54
#Mann= 7 ,-1 , 0
       0     .12       0  913.05     .99       0 2528.79     .12       0
 2720.57    .045       0 2805.81     .12       0 3245.46     .99       0
 4094.35     .12       0
#XS Ineff= 2 , 0
       0 2731.75      17 2772.25       0      17
Permanent Ineff=
       F       F
#Block Obstruct= 2 , 0
       0     910      22    4110       0      22
Bank Sta=2733.2,2771.3
XS Rating Curve= 0
Exp/Cntr=.5,.3

Type RM Length L Ch R = 1 ,15493.04,172.61,124.8,41.72
BEGIN DESCRIPTION:
Copy of 471s11 u.  XS 1/4.
Bank Station offset =      2264
Set special ineffective on LOB as this will not effectively convey flow unless Barbours Cut Blvd just d/s is overtopped on LOB.(El. 19.6 to 20.0)
END DESCRIPTION:
XS GIS Cut Line= 6
     3226936.969    13816318.607     3226958.184    13816175.744
      3227064.53    13813517.098     3226916.422    13813254.437
     3226122.201      13812226.3     3225786.289    13811841.938
#Sta/Elev= 30
       0   21.83  710.99   21.12  801.63   19.35  1819.4   17.91 1849.42   15.69
 1877.18   17.79 1950.63   18.14 2595.48   17.05 2668.59   17.41 2714.17   16.33
 2728.38   12.88  2729.1   11.19 2736.06   10.81 2752.27   16.29 2786.78   17.11
 3257.55   19.67 3317.08   17.92  4083.2   19.48  4110.7   24.65 4159.77   41.12
 4173.91   34.87 4184.83   32.62 4191.52   28.57 4222.74   20.26 4356.06   20.59
 4405.14   18.77  4539.8   20.93 4575.51   18.67 4724.36   18.31 4916.98   20.05
#Mann= 7 ,-1 , 0
       0     .12       0  710.99     .99       0 2595.48     .12       0
 2668.59    .045       0 2786.78     .12       0 3257.55     .99       0
 4159.77     .12       0
#Block Obstruct= 2 , 0
       0     630      22    4150       0      22
Bank Sta=2714.17,2752.27
XS Rating Curve= 0
Exp/Cntr=.3,.1

Type RM Length L Ch R = 1 ,15368.24,197.07,91.51,34.47
BEGIN DESCRIPTION:
Copy of 471s10 d.  XS 4/4.
Bank Station offset =      2075
cross section extended on LOB
Set special ineffective on LOB as this will not effectively convey flow unless Barbours Cut Blvd just d/s is overtopped on LOB.(El. 19.6 to 20.0)
END DESCRIPTION:
XS GIS Cut Line= 6
     3228086.671    13816379.653     3227202.025    13813872.075
     3227182.673    13813571.838     3227074.214    13813407.906
     3226128.711    13812198.399 3225760.763480513811762.0931236
#Sta/Elev= 30
       0   21.26 1185.75   19.71 1959.34   19.28 1996.48   16.44 2051.98   18.54
 2248.02   16.79 2863.36   17.56 2901.29   16.58  2925.3    10.6 2942.19   15.77
 2984.68   17.13 2988.58   19.18  3016.7   16.25 3177.22   18.87 3533.88   19.49
 4348.45      19 4396.08   22.08 4409.19   24.36 4433.89   33.24 4455.26   24.27
 4472.24    20.7 4491.28   22.94 4508.69   29.51 4560.05   19.89 4652.74   20.56
 4701.02   18.77 4826.66   20.84 4866.17   18.64 5026.79   18.28    5263      21
#Mann= 6 ,-1 , 0
       0     .12       0 1185.75     .99       0 2863.36    .045       0
 2984.68     .12       0 3533.88     .99       0 4433.89     .12       0
#Block Obstruct= 2 , 0
       0     880      22    4430       0      22
Bank Sta=2901.29,2942.19
XS Rating Curve= 0
Exp/Cntr=.5,.3

Type RM Length L Ch R = 1 ,15276.72,49.81,46.36,28.35
BEGIN DESCRIPTION:
 XS3/4. (Copy of 471s10d:)
Bank Station offset =      1958
Sta 1950 did not block the 500 yr b/c high point is an island.
Set special ineffective on LOB as this will not effectively convey flow unless Barbours Cut Blvd just d/s is overtopped on LOB.(El. 19.6 to 20.0)
END DESCRIPTION:
XS GIS Cut Line= 6
     3228330.856    13816374.566     3227545.763    13814200.075
     3227369.988    13813603.172     3227240.132    13813583.789
     3227192.154    13813537.222     3225805.332    13811708.226
#Sta/Elev= 30
       0   20.51   698.9   20.91  775.79   22.84  999.15   20.16 1492.58   20.82
 1883.85   18.82 1926.96   19.05 1954.41   21.89 1990.95   16.57 2022.94    19.4
 2486.63   16.74 2870.39   17.56 2947.82   14.91 2980.12   17.41 3030.72   14.43
 3042.06   10.45 3058.95   15.62 3101.44   16.98 3102.37   20.04 3106.47   20.12
 3146.52   16.35 3609.32   19.43 4576.82   18.92 4614.99   22.38 4622.17   26.35
  4640.9    31.2 4712.83   32.58 4730.62   32.31 4780.71   19.91 5431.41   19.39
#Mann= 7 ,-1 , 0
       0     .12       0 1492.58     .99       0 2870.39     .12       0
 2980.12    .045       0 3101.44     .12       0 3609.32     .99       0
 4712.83     .12       0
#XS Ineff= 2 , 0
       0    3025   19.52    3060       0   19.52
Permanent Ineff=
       F       F
#Block Obstruct= 2 , 0
       0    1470      22    4680       0      22
Bank Sta=3030.72,3058.95
XS Rating Curve= 0
Exp/Cntr=.5,.3

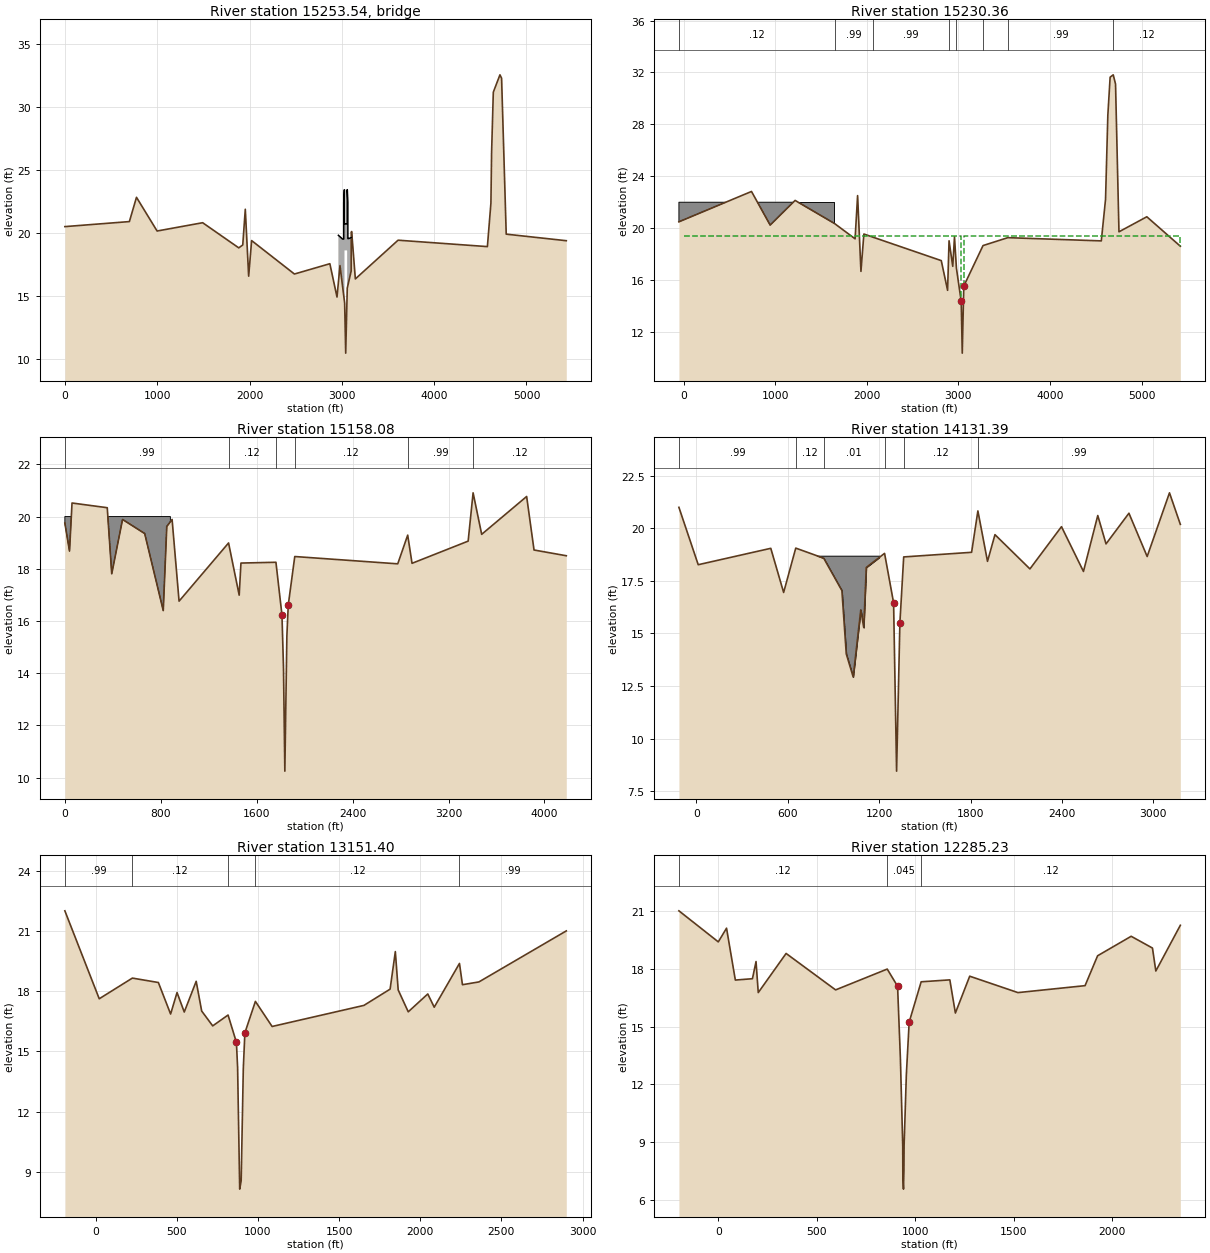
Type RM Length L Ch R = 3 ,15253.54,,,
BEGIN DESCRIPTION:
Barbours Cut Blvd., 471s10, concrete bridge
Roadway has steep edges in profile due to cross sections not being over roadway.
'Distance from upstream XS' of 3.9 being less than bridge opening of 7.45 is not considered to impact the model.  The cross sections are located outside the foot of the embankments.
END DESCRIPTION:
Bridge Culvert--1,0,-1,-1, 0
Deck Dist Width WeirC Skew NumUp NumDn MinLoCord MaxHiCord MaxSubmerge Is_Ogee
3.9,38.5,2.6,0, 16, 16, 19.52, , .95, 0, 0,0,,
 2962.66 3008.61 3020.64 3020.64 3026.41 3028.53 3028.53  3029.7 3056.43 3057.63
 3057.63 3059.58 3065.56 3065.56 3075.43    3102
   19.82   19.52   19.52   22.41   23.44   23.44   20.72   20.72   20.72   20.72
   23.45   23.43   22.44   19.56   19.56   19.64
       0       0       0       0       0       0   18.62   18.62   18.62   18.62
       0       0       0       0       0       0
 2962.66 3008.61 3020.64 3020.64 3026.41 3028.53 3028.53  3029.7 3056.43 3057.63
 3057.63 3059.58 3065.56 3065.56 3075.43 3098.65
   19.82   19.52   19.52   22.41   23.44   23.44   20.72   20.72   20.72   20.72
   23.45   23.43   22.44   19.56   19.56   19.64
       0       0       0       0       0       0   18.62   18.62   18.62   18.62
       0       0       0       0       0       0
BR Coef=-1 , 0 , 0 ,, 0 ,,,.8,0,,0,
WSPro=,,,, 1 ,,,, 0 ,,,, 0 ,,,,-1 ,-1 ,-1 , 0 , 0 , 0 , 0 , 0
BC Design=,, 0 ,, 0 ,,,,,,

Type RM Length L Ch R = 1 ,15230.36,87.69,72.29,37.87
BEGIN DESCRIPTION:
Copy of 471s10 d.  XS 2/4. .
Bank Station offset =      1905
Sta 1950 did not block the 500 yr b/c high point is an island
END DESCRIPTION:
XS GIS Cut Line= 6
     3228356.292    13816369.479     3227545.763    13814154.075
     3227372.135    13813547.771     3227249.552    13813539.834
     3227192.154    13813491.222      3225823.96     13811658.55
#Sta/Elev= 30
     -53   20.49  739.85   22.83  943.59   20.24 1216.07   22.14 1648.69   20.35
  1871.4   19.18 1898.88   22.51 1935.39   16.67 1967.38   19.55 2069.69    19.3
 2812.83    17.5 2881.77   15.21 2897.73   19.03 2938.08   17.06 2957.18   19.32
 2978.18   16.92 3030.65   14.35 3041.99   10.37 3058.88   15.54 3268.95   18.66
 3539.75   19.27 4560.85   19.02 4607.17   22.23 4632.21   28.71 4657.26   31.64
 4691.07   31.82 4716.35   31.11 4753.81   19.72 5058.01   20.88 5424.17   18.61
#Mann= 8 ,-1 , 0
     -53     .12       0 1648.69     .99       0 2069.69     .99       0
 2897.73     .12       0 2978.18    .045       0 3268.95     .12       0
 3539.75     .99       0 4691.07     .12       0
#XS Ineff= 2 , 0
       0    3025   19.39    3060       0   19.39
Permanent Ineff=
       F       F
#Block Obstruct= 2 , 0
     -53    1642      22    4667     -53      22
Bank Sta=3030.65,3058.88
XS Rating Curve= 0
Exp/Cntr=.5,.3

Type RM Length L Ch R = 1 ,15158.08,1012.47,1026.69,836.48
BEGIN DESCRIPTION:
471s10 d.  XS 1/4
Bank Station offset =      3165
END DESCRIPTION:
XS GIS Cut Line= 6
     3228897.673    13814154.777     3228210.181    13813614.189
     3228057.718    13813534.643     3227209.481    13813463.933
     3227157.847    13813355.897     3225848.798    13811633.712
#Sta/Elev= 30
       0   19.75   38.84   18.68   59.79   20.52  353.48   20.34  390.92   17.81
  481.24   19.89  665.78   19.35  820.57    16.4  850.04   19.62   894.3   19.89
   952.5   16.76 1365.26   18.99 1453.89   16.99 1468.59   18.22 1760.34   18.25
 1810.59   16.23 1823.26   14.23  1834.6   10.25 1851.49   15.42 1863.04   16.61
 1917.34   18.47 2776.15   18.19 2859.18   19.29  2895.3   18.21 3363.34   19.06
 3404.56   20.91 3476.21   19.32 3851.21   20.77 3912.78   18.72 4181.79    18.5
#Mann= 6 ,-1 , 0
       0     .99       0 1365.26     .12       0 1760.34    .045       0
 1917.34     .12       0 2859.18     .99       0 3404.56     .12       0
#Block Obstruct= 2 , 0
       0     880      20    3390       0      21
Bank Sta=1810.59,1863.04
XS Rating Curve= 0
Exp/Cntr=.3,.1

Type RM Length L Ch R = 1 ,14131.39,913.05,979.99,877.14
BEGIN DESCRIPTION:
471v13
Bank Station offset =      3686
Extended cross section on LOB
Lateral stream blocked with low mannings
END DESCRIPTION:
XS GIS Cut Line= 6
 3228984.904497313813103.7973345     3227925.484    13812636.241
     3227737.371    13812602.826     3227580.982    13812566.752
     3227344.726    13812463.658     3226122.017    13811552.988
#Sta/Elev= 30
    -115      21   11.76   18.27  488.21   19.05  572.61   16.95  652.17   19.06
  835.93   18.58  955.09   17.04  983.81   14.03 1029.39   12.93 1079.18   16.12
 1098.69   15.28 1115.28   18.14  1235.3   18.81 1294.56   16.46 1314.26    8.45
 1335.99   15.51 1360.89   18.64 1806.76   18.86 1848.05   20.83 1911.19   18.43
 1960.22    19.7 2189.76   18.07 2396.88   20.08 2541.24   17.95 2635.19   20.61
 2689.36   19.26 2839.78   20.72 2959.48   18.66 3106.05   21.69 3177.34   20.19
#Mann= 6 ,-1 , 0
    -115     .99       0  652.17     .12       0  835.93     .01       0
  1235.3    .045       0 1360.89     .12       0 1848.05     .99       0
#Block Obstruct= 1 ,-1
     780    1200    18.7
Bank Sta=1294.56,1335.99
XS Rating Curve= 0
Exp/Cntr=.3,.1

Type RM Length L Ch R = 1 ,13151.40,871.5,866.17,874.66
BEGIN DESCRIPTION:
471v12
Bank Station offset =      4113
The high point on the ROB is due to a building and observed that it is not continuous. Hence not made ineffective (n=0.99)
Extended cross section on LOB
Extended XS on ROB
END DESCRIPTION:
XS GIS Cut Line= 6
 3229124.404562613811981.9061475     3228641.073    13811849.678
     3228295.668     13811781.04     3227977.342    13811755.382
     3226980.481    13811551.613 3226096.139533213811385.1147163
#Sta/Elev= 30
    -190      22   21.83   17.62  226.06   18.65  386.23   18.43  461.66   16.86
  501.31   17.93  545.82   16.96  619.28   18.49   653.1   17.01  721.13   16.27
  815.71   16.81  867.17   15.45  874.55   14.19  887.43    8.14  896.47    8.55
  909.66   14.15  919.26   15.92  984.14   17.49 1087.12   16.24 1652.92   17.29
 1814.31    18.1 1846.49   19.97 1864.09   18.06 1926.05   16.97  2046.5   17.86
 2086.14    17.2 2241.76   19.38 2260.11   18.32 2361.86   18.46    2900      21
#Mann= 5 ,-1 , 0
    -190     .99       0  226.06     .12       0  815.71    .045       0
  984.14     .12       0 2241.76     .99       0
#Block Obstruct= 2 , 0
       0                    2241       0    19.4
Bank Sta=867.17,919.26
XS Rating Curve= 0
Exp/Cntr=.3,.1

Type RM Length L Ch R = 1 ,12285.23,60.47,72.03,69.85
BEGIN DESCRIPTION:
471s9u:  XS 4/4.
Bank Station offset =      4060
Extended XS on LOB
END DESCRIPTION:
XS GIS Cut Line= 6
  3229184.60367313810964.0487734     3228730.456    13810961.858
     3228314.012    13810937.217     3228131.588    13810898.581
     3227022.346    13810892.326     3226643.617    13810900.988
#Sta/Elev= 30
    -200      21       0   19.39   41.85    20.1   86.56   17.41  173.36   17.48
  191.56   18.37   202.9   16.76  344.32   18.79  595.67    16.9   857.8   17.98
  910.32   17.09  924.67   13.34  936.53    8.83  937.15    7.16  940.28    6.57
  942.61    7.52  943.51    8.85   954.9   12.51  969.23   15.23 1030.07   17.32
 1175.71   17.42 1203.88    15.7 1276.59   17.61 1521.56   16.76 1862.33   17.12
 1926.06   18.67 2096.47   19.68 2204.63   19.07 2221.72   17.88 2346.18   20.25
#Mann= 3 ,-1 , 0
    -200     .12       0   857.8    .045       0 1030.07     .12       0
#Block Obstruct= 2 , 0
       0                    2095       0      20
Bank Sta=910.32,969.23
XS Rating Curve= 0
Exp/Cntr=.5,.3