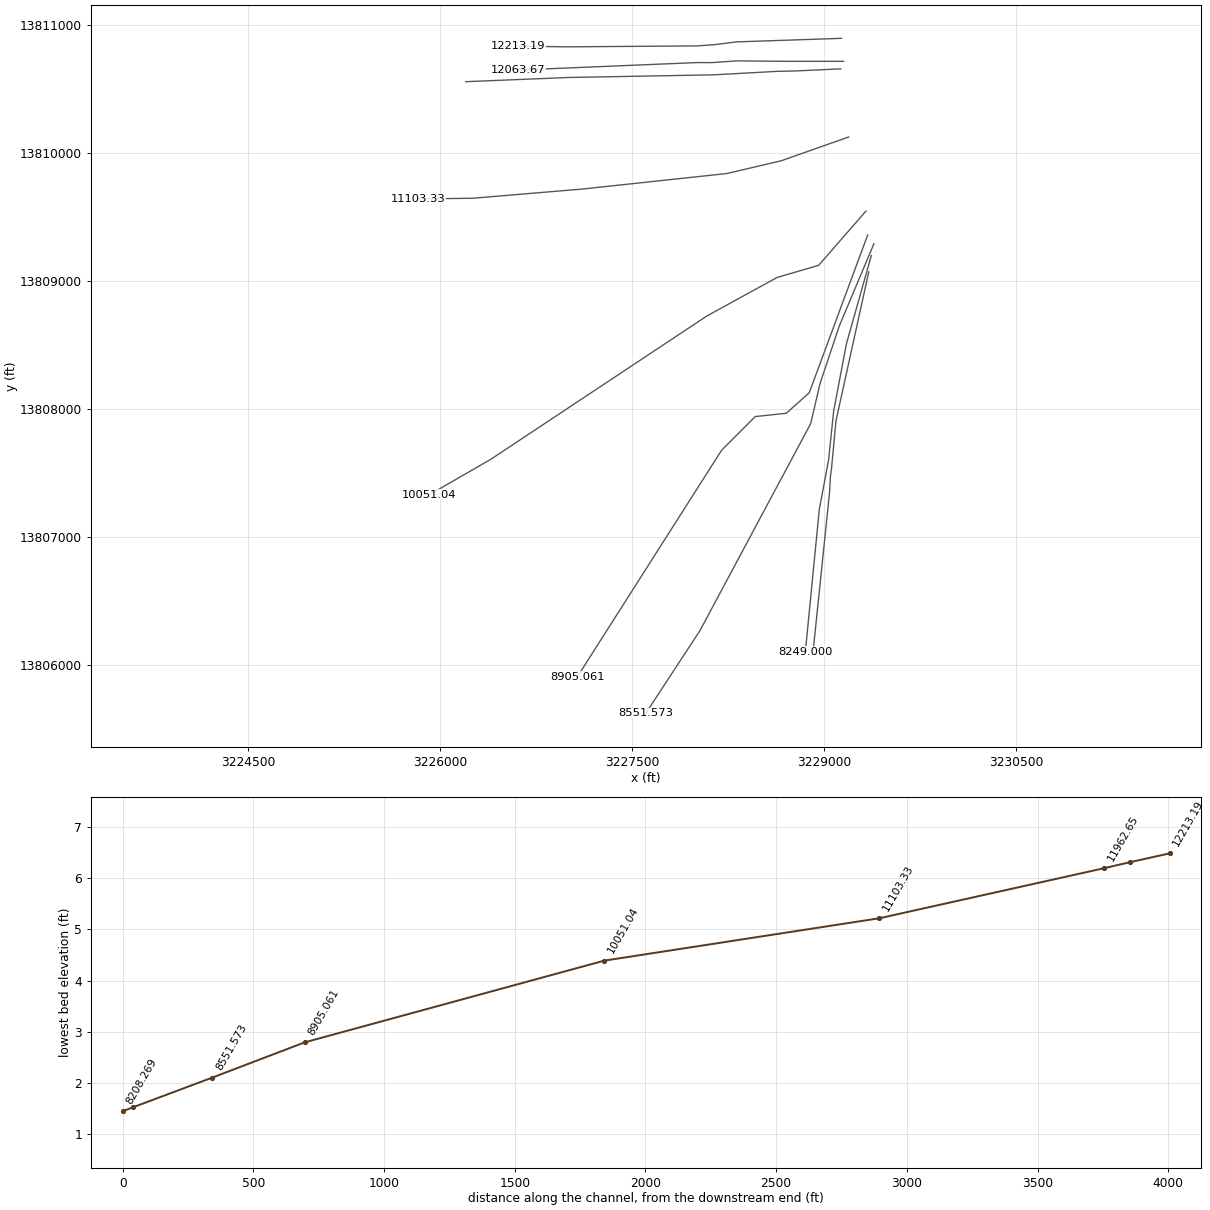
HEC-RAS study F216-00-00.prj: F216-00-00

--- F216-00-00.g03 (geometry) --- (continued)

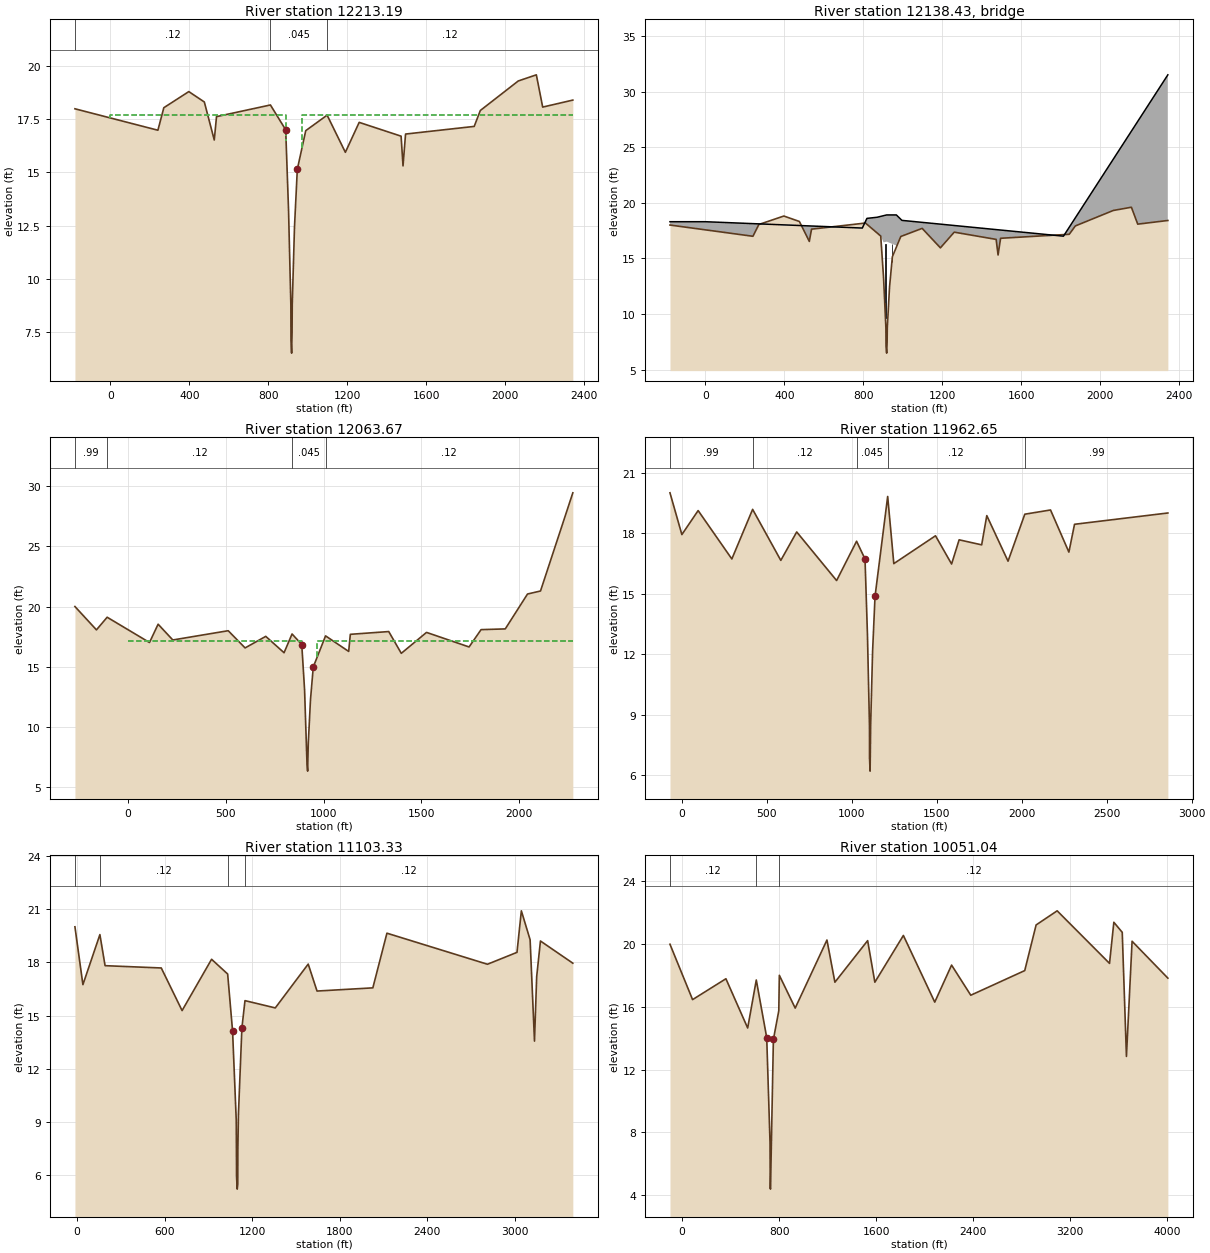
Type RM Length L Ch R = 1 ,12213.19,142.16,149.53,139.3
BEGIN DESCRIPTION:
Copy of 471s9u:  XS 3/4.
Bank Station offset =      4082
Extended cross section on LOB
LOB block due to flow not being conveyed downstream.
END DESCRIPTION:
XS GIS Cut Line= 6
 3229133.475474713810894.0518933     3228314.012    13810866.217
     3228144.594    13810844.994     3228009.036    13810834.976
     3226997.596    13810827.645     3226612.569    13810832.684
#Sta/Elev= 30
    -180      18  240.48   16.99  270.46   18.05  397.11   18.81  475.79   18.32
  526.09   16.53   537.5   17.63  810.68   18.18  888.05   17.01   902.4   13.26
  914.26    8.75  914.88    7.08  918.01    6.49  920.34    7.44  921.24    8.77
  932.63   12.43  946.96   15.15  989.69   16.97 1097.96    17.7 1190.45   15.95
  1260.5   17.36  1472.9   16.71 1482.61   15.31 1495.46   16.81 1843.38   17.17
  1874.4   17.92 2066.55   19.31 2158.29    19.6 2190.41   18.08 2343.14   18.41
#Mann= 3 ,-1 , 0
    -180     .12       0  810.68    .045       0 1097.96     .12       0
#XS Ineff= 2 , 0
       0     890   17.73     970       0   17.73
Permanent Ineff=
       F       F
#Block Obstruct= 2 , 0
       0    -175      20    2150       0      20
Bank Sta=888.05,946.96
XS Rating Curve= 0
Exp/Cntr=.5,.3

Type RM Length L Ch R = 3 ,12138.43,,,
BEGIN DESCRIPTION:
(W.) Main St., 471s9, concrete bridge
Calculated LC from TOR
Bridge opening ~115 ft, added ground pts. at low chord elev. to define opening.
Top of deck/roadway extensions assumed based on aerial photos and GIS tin elevations.  Tall road embankment located on far ROB for this structure.
END DESCRIPTION:
Bridge Culvert--1,0,-1,-1, 0
Deck Dist Width WeirC Skew NumUp NumDn MinLoCord MaxHiCord MaxSubmerge Is_Ogee
26.2,97,2.6,0, 11, 10, 18.56, , .95, 0, 0,0,,
    -180       0  794.64  818.01  869.59     918  967.13  967.13  995.47    1814
    2343
    18.3    18.3   17.73    18.6    18.7   18.91   18.91   18.91   18.42      17
    31.5
       0       0       0    16.3    16.3   16.51   16.16       0       0       0
       0
    -200  794.64  818.01  869.59     918  967.13  967.13  995.47    1743    2273
    18.3   17.73    18.6    18.7   18.91   18.91   18.91   18.42      17    31.5
       0       0    16.3    16.3   16.51   16.16       0       0       0       0
Pier Skew, UpSta & Num, DnSta & Num=  ,911.93, 4 ,911.93, 4 , 3 , 3 , 0 ,0,
     1.5     1.5     2.5     2.5
    9.79    13.8    13.8    16.3
     1.5     1.5     2.5     2.5
    9.79    13.8    13.8    16.3
Pier Skew, UpSta & Num, DnSta & Num=  ,944.68, 4 ,944.68, 4 , 3 , 3 , 0 ,0,
     1.5     1.5     2.5     2.5
    9.79      14      14    16.5
     1.5     1.5     2.5     2.5
    9.79      14      14    16.5
BR Coef=-1 , 0 , 0 ,, 0 ,,,.8,0,,0,
WSPro=,,,, 1 ,,,, 0 ,,,, 0 ,,,,-1 ,-1 ,-1 , 0 , 0 , 0 , 0 , 0
BC Design=,, 0 ,, 0 ,,,,,,

Type RM Length L Ch R = 1 ,12063.67,97.94,101.02,94.19
BEGIN DESCRIPTION:
Copy of 471s9u:  XS 2/4.
Bank Station offset =      3920
Extended XS on LOB
END DESCRIPTION:
XS GIS Cut Line= 6
  3229150.49199913810714.7178207     3228699.077    13810714.657
     3228316.931    13810718.009     3228121.918    13810704.403
     3228009.036    13810704.976      3226606.36    13810646.398
#Sta/Elev= 30
    -272      20    -162   18.06 -107.21   19.11  109.23   17.01  153.37   18.53
  228.43   17.22  511.74   17.99  598.06   16.56  703.73   17.52  797.34   16.16
  838.21   17.72  887.85   16.84   902.2   13.09  914.68    6.91  917.81    6.32
  921.04     8.6  932.43   12.26  946.76   14.98 1009.53   17.56 1127.73   16.27
 1136.15   17.69 1332.55   17.92 1396.76   16.11 1525.79   17.85 1743.31   16.64
 1804.73   18.08 1928.45   18.14 2042.14   21.04  2108.6   21.29 2273.85   29.45
#Mann= 4 ,-1 , 0
    -272     .99       0 -107.21     .12       0  838.21    .045       0
 1009.53     .12       0
#XS Ineff= 2 , 0
       0     888    17.1   967.3       0    17.1
Permanent Ineff=
       F       F
Bank Sta=887.85,946.76
XS Rating Curve= 0
Exp/Cntr=.5,.3

Type RM Length L Ch R = 1 ,11962.65,824.69,859.32,818.02
BEGIN DESCRIPTION:
Copy of 471s9u:  XS1/4.
Bank Station offset =      3892
Cross Section extended on LOB
Cross Section extended to edge of watershed on ROB
END DESCRIPTION:
XS GIS Cut Line= 6
 3229129.043157413810655.8870327     3228773.502    13810639.214
     3228634.395    13810636.375     3228140.058    13810609.164
     3227003.908    13810588.327 3226201.090893413810555.6323619
#Sta/Elev= 30
     -70      20       0   17.93   95.72   19.12  294.08   16.72  416.41   19.18
  582.23   16.65  675.83   18.06  910.64   15.65 1028.11    17.6 1077.75   16.72
  1092.1   12.97 1103.96    8.46 1104.58    6.79 1107.71     6.2 1110.94    8.48
 1122.33   12.14 1136.66   14.86 1211.08   19.82 1247.26   16.49 1492.53   17.87
 1587.31   16.47 1631.57   17.67 1764.27   17.42 1794.37   18.87 1919.42   16.61
 2018.05   18.94 2169.46   19.15 2277.56   17.06 2310.71   18.44    2860      19
#Mann= 5 ,-1 , 0
     -70     .99       0  416.41     .12       0 1028.11    .045       0
 1211.08     .12       0 2018.05     .99       0
Bank Sta=1077.75,1136.66
XS Rating Curve= 0
Exp/Cntr=.3,.1

Type RM Length L Ch R = 1 ,11103.33,991.9,1052.28,1085.31
BEGIN DESCRIPTION:
471v11
Bank Station offset =      3902
cross section extended on LOB
END DESCRIPTION:
XS GIS Cut Line= 6
 3229191.194043213810123.7257436     3228662.548    13809937.469
     3228238.183    13809838.224     3227112.481    13809717.341
     3226253.587    13809645.165      3225830.17    13809640.456
#Sta/Elev= 30
     -15      20   39.71   16.74  156.19   19.56   191.7   17.81  577.02   17.68
   719.8   15.28  922.02   18.17 1032.21   17.34  1065.9   14.13 1091.09    9.11
 1093.34    5.92 1097.62    5.22 1101.62    5.49  1102.3    7.49 1106.11    9.44
 1129.81    14.3 1151.04   15.84 1358.81   15.43 1584.61    17.9 1645.01   16.38
 2027.78   16.56 2124.33   19.64  2813.7   17.89 3016.14   18.56 3046.14    20.9
 3106.15   19.27 3136.15   13.56 3151.15   17.19 3177.03    19.2 3399.04   17.95
#Mann= 4 ,-1 , 0
     -15     .99       0  156.19     .12       0 1032.21    .045       0
 1151.04     .12       0
#Block Obstruct= 2 , 0
       0                    2120       0      21
Bank Sta=1065.9,1129.81
XS Rating Curve= 0
Exp/Cntr=.3,.1

Type RM Length L Ch R = 1 ,10051.04,1168.37,1145.99,1103.94
BEGIN DESCRIPTION:
471v10
Bank Station offset =      4271
XS extended on LOB
END DESCRIPTION:
XS GIS Cut Line= 6
 3229325.651131913809545.3509977     3228956.052    13809121.162
     3228633.668    13809027.781     3228084.712    13808726.766
     3226396.956     13807607.35     3225917.103    13807330.514
#Sta/Elev= 30
    -100      20   86.33   16.47  361.32    17.8  540.79   14.66  611.83   17.72
  697.76   14.05  725.07    7.37  726.82    4.45  728.97    4.39  752.79   13.93
  797.33   15.76  801.84   18.02  932.63   15.93 1194.52   20.27 1260.08   17.58
 1529.98   20.23  1589.6   17.58 1824.79   20.56 2083.51   16.31 2222.26   18.67
 2380.55   16.75 2825.52   18.32 2919.38   21.23    3093   22.13 3524.77   18.78
 3560.33    21.4  3629.6   20.76 3664.23   12.85 3710.77   20.19 4005.89   17.84
#Mann= 3 ,-1 , 0
    -100     .12       0  611.83    .045       0  801.84     .12       0
#Block Obstruct= 2 , 0
       0                    1030       0    18.5
Bank Sta=697.76,752.79
XS Rating Curve= 0
Exp/Cntr=.3,.1

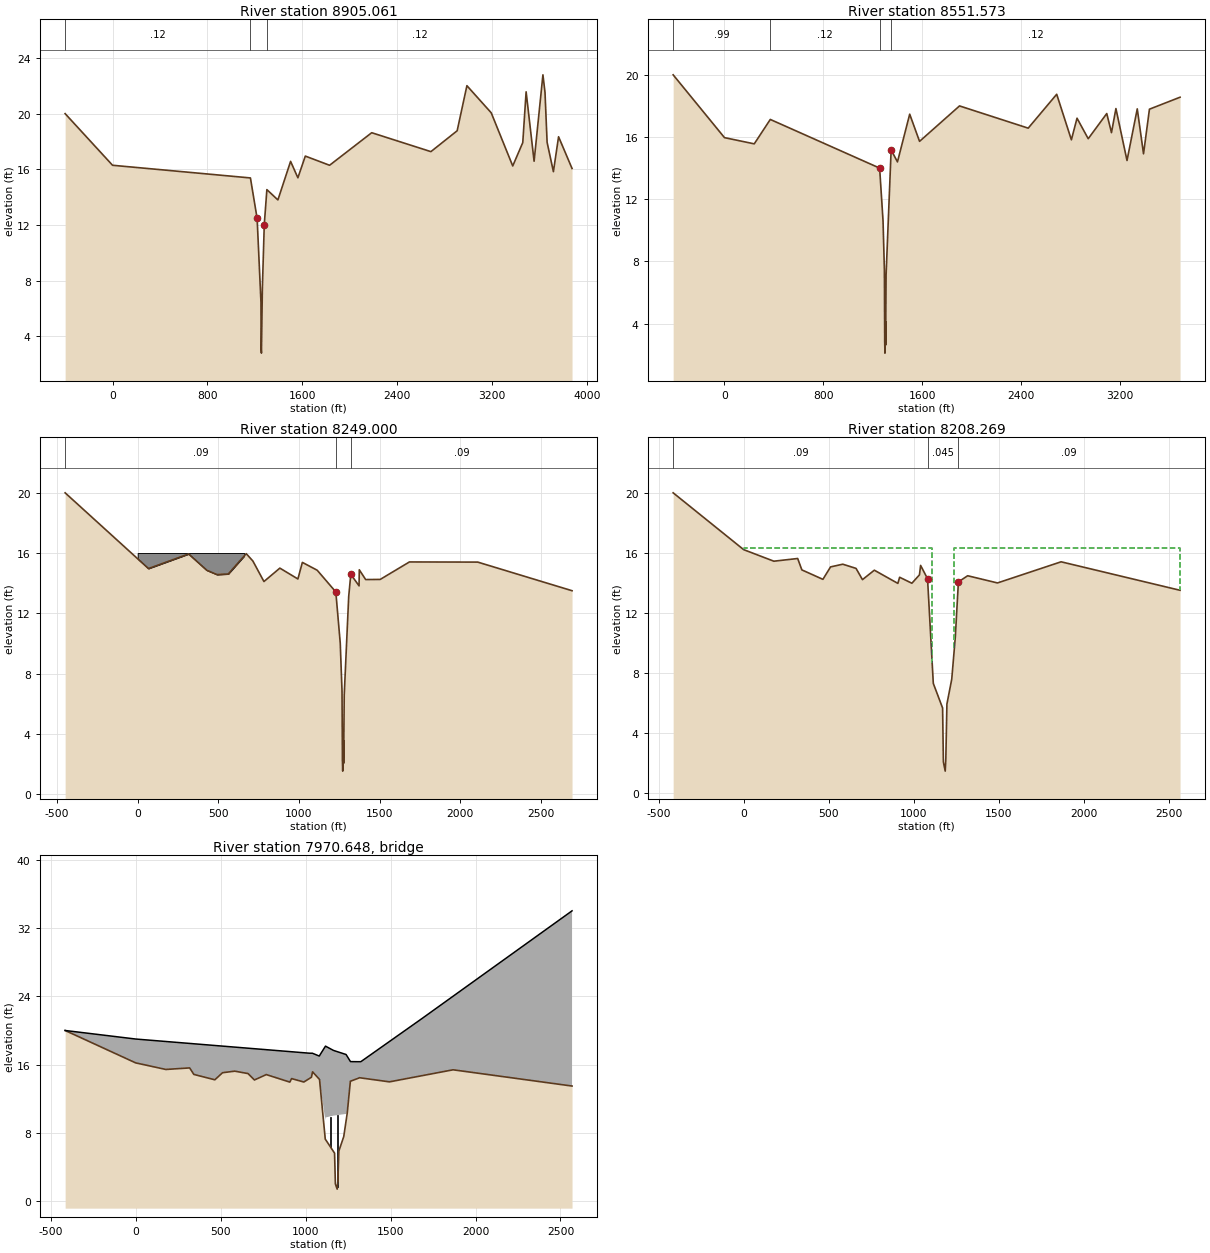
Type RM Length L Ch R = 1 ,8905.061,290.19,353.49,379.11
BEGIN DESCRIPTION:
471v9
Bank Station offset =      3744
Removed Lidar data from sta 1088 to 1154 based on aerial photo.
Extended cross section on LOB
END DESCRIPTION:
XS GIS Cut Line= 6
 3229338.949148513809358.0504316     3228882.847    13808126.416
     3228703.515    13807966.482     3228461.017    13807940.525
      3228199.34    13807678.848     3227072.074    13805908.534
#Sta/Elev= 30
    -400      20       0   16.29 1163.04   15.38 1219.58   12.47 1251.99    6.45
 1253.55    3.08 1255.85    2.79 1263.85    7.47 1279.76   12.01 1301.84   14.54
 1394.81    13.8 1501.94   16.57 1563.42   15.39 1626.07   16.95 1830.73   16.29
 2186.13   18.63 2685.55   17.27 2907.02   18.77 2989.24   22.01 3194.36   20.06
 3375.82   16.24 3460.46   17.92 3488.68   21.57 3556.03   16.58 3630.44   22.79
    3648   21.53 3665.71   17.94 3718.84   15.83 3762.46   18.34 3876.11   16.06
#Mann= 3 ,-1 , 0
    -400     .12       0 1163.04    .045       0 1301.84     .12       0
#Block Obstruct= 2 , 0
       0                    3190       0      20
Bank Sta=1219.58,1279.76
XS Rating Curve= 0
Exp/Cntr=.3,.1

Type RM Length L Ch R = 1 ,8551.573,304.38,302.57,312.58
BEGIN DESCRIPTION:
Copy of 471s8u:  XS 4/4.
Bank Station offset =      3703
Extended XS on LOB
END DESCRIPTION:
XS GIS Cut Line= 6
 3229387.860327913809290.1939739     3229118.231     13808650.01
     3228966.893    13808197.963     3228894.478    13807886.019
     3228028.935    13806268.376     3227606.093    13805622.896
#Sta/Elev= 30
    -415      20       0   15.96  240.69   15.56  370.34   17.13 1254.48      14
    1282    10.6 1292.92    7.43  1295.5    2.79 1297.33     2.1  1302.8    4.12
    1303    2.62 1306.65    7.14 1347.45   15.17 1398.65    14.4 1497.54   17.47
 1577.15   15.72 1900.35      18 2455.76   16.57 2686.07   18.75 2804.79   15.82
 2850.42   17.21 2940.89   15.89 3090.83   17.51 3129.03   16.28  3164.9   17.83
 3254.56   14.49 3337.43   17.81 3388.07   14.92 3435.93   17.79 3683.54   18.56
#Mann= 4 ,-1 , 0
    -415     .99       0  370.34     .12       0 1254.48    .045       0
 1347.45     .12       0
#Block Obstruct= 2 , 0
       0                    2680       0      18
Bank Sta=1254.48,1347.45
XS Rating Curve= 0
Exp/Cntr=.5,.3

Type RM Length L Ch R = 1 ,8249.000,35.53,40.73,46.69
BEGIN DESCRIPTION:
471s8u:  XS 3.1/4.
Bank Station offset =      3728
Extended XS on LOB
Higher c/e coefficients used to avoid negative slope in WS profiles
END DESCRIPTION:
XS GIS Cut Line= 6
  3229367.68218713809197.9817406     3229173.676    13808510.865
     3229073.398    13807983.465     3229033.867    13807601.588
     3228961.208    13807214.809 3228852.726060313806105.8473562
#Sta/Elev= 30
    -450      20   66.81   14.97  315.96   15.94  428.14   14.86  491.97   14.57
  561.77   14.61  673.31   15.96  714.56   15.47   783.1   14.11  881.88      15
  993.64   14.28 1021.44   15.38 1113.41   14.86 1228.82   13.42 1256.34   10.02
 1267.26    6.85 1269.84    2.21 1271.67    1.52 1277.14    3.54 1277.34    2.04
 1280.99    6.56 1308.75   13.11 1321.79   14.59 1372.99   13.82 1374.49   14.89
 1413.87   14.24 1504.39   14.25 1685.29   15.41    2109    15.4    2694    13.5
#Mann= 3 ,-1 , 0
    -450     .09       0 1228.82    .045       0 1321.79     .09       0
#Block Obstruct= 2 , 0
       0     660      16    2100       0    15.5
Bank Sta=1228.82,1321.79
XS Rating Curve= 0
Exp/Cntr=.7,.5

Type RM Length L Ch R = 1 ,8208.269,472.16,475.24,489.41
BEGIN DESCRIPTION:
Copy of 471s6u:  XS 3/4.
Bank Station offset =      3814
Extended XS on LOB
END DESCRIPTION:
XS GIS Cut Line= 6
 3229347.680520313809070.7165078      3229091.43    13807906.655
     3229056.551    13807533.534     3229048.044    13807471.152
     3229042.373     13807357.73 3228914.805785213806124.5502641
#Sta/Elev= 30
    -415      20       0   16.21  177.54   15.44  317.76   15.62  342.38   14.86
  466.19   14.23  511.26   15.06  583.21   15.24  661.23   14.96  699.01   14.21
  768.76   14.84  907.31   13.96  917.64   14.37  989.85   13.97 1034.38   14.53
 1041.21   15.16 1081.98   14.27 1115.85    7.29 1170.57    5.65 1175.23    2.05
 1185.98    1.44 1189.57    2.26 1195.94    5.91 1224.47    7.58 1245.41   10.38
 1263.56   14.06 1318.06   14.47 1493.58   13.99    1868    15.4    2568    13.5
#Mann= 3 ,-1 , 0
    -415     .09       0 1081.98    .045       0 1263.56     .09       0
#XS Ineff= 2 , 0
       0    1110   16.35    1240       0   16.35
Permanent Ineff=
       F       F
Bank Sta=1081.98,1263.56
XS Rating Curve= 0
Exp/Cntr=.5,.3

Type RM Length L Ch R = 3 ,7970.648,,,
BEGIN DESCRIPTION:
State Hwy 146, 471s5,
 471s6, 471s7, & 471s8
D/S internal XS based on 4715c
U/S internal XS based on 4716u
High chord based on 471s6 top of rail, and 471s7 TR
D/S low chord based on low chord of 471s5.
Top of deck/roadway extensions assumed based on aerial photos and GIS tin elevations.
U/S low chord based on low chord of 471s8c, brought g.s. up to low chord to define channel U/S
Piers based on description of 471s5 & adjusted U/S for 471s8 low chord elev.
END DESCRIPTION:
Bridge Culvert--1,0,-1,-1, 0
Deck Dist Width WeirC Skew NumUp NumDn MinLoCord MaxHiCord MaxSubmerge Is_Ogee
19.1,437,2.6,0, 13, 8, 17.19, , .95, 0, 0,0,,
    -415       1    1025 1040.06 1080.35 1117.04 1164.04 1238.25 1264.18  1303.5
    1325    1685    2568
      20      19   17.34   17.34   17.01   18.17   17.67   17.19   16.36   16.35
   16.35    21.4      34
       0       0       0       0       0    9.82   10.04   10.24       0       0
       0       0
    -499 1054.06 1094.35 1121.22 1201.63 1278.18  1317.5    1701
    20.5   17.34   17.01   18.17   17.67   17.19   16.35      25
       0       0       0    9.97    9.82    9.88       0       0
Pier Skew, UpSta & Num, DnSta & Num=  ,1146.13, 4 ,1141.27, 4 , 3 , 3 , 0 ,0,
    1.35    1.35     2.8     2.8
     6.9    7.35    7.35     9.9
    1.35    1.35     2.8     2.8
     6.4    7.27    7.27    9.82
Pier Skew, UpSta & Num, DnSta & Num=  ,1187.31, 4 ,1182.45, 4 , 3 , 3 , 0 ,0,
    1.35    1.35     2.8     2.8
    6.38    7.63    7.63   10.18
    1.35    1.35     2.8     2.8
    5.68    7.35    7.35    9.85
BR Coef=-1 , 0 , 0 ,, 0 ,,,.8,0,,0,
WSPro=,,,, 1 ,,,, 0 ,,,, 0 ,,,,-1 ,-1 ,-1 , 0 , 0 , 0 , 0 , 0
BC Design=,, 0 ,, 0 ,,,,,,