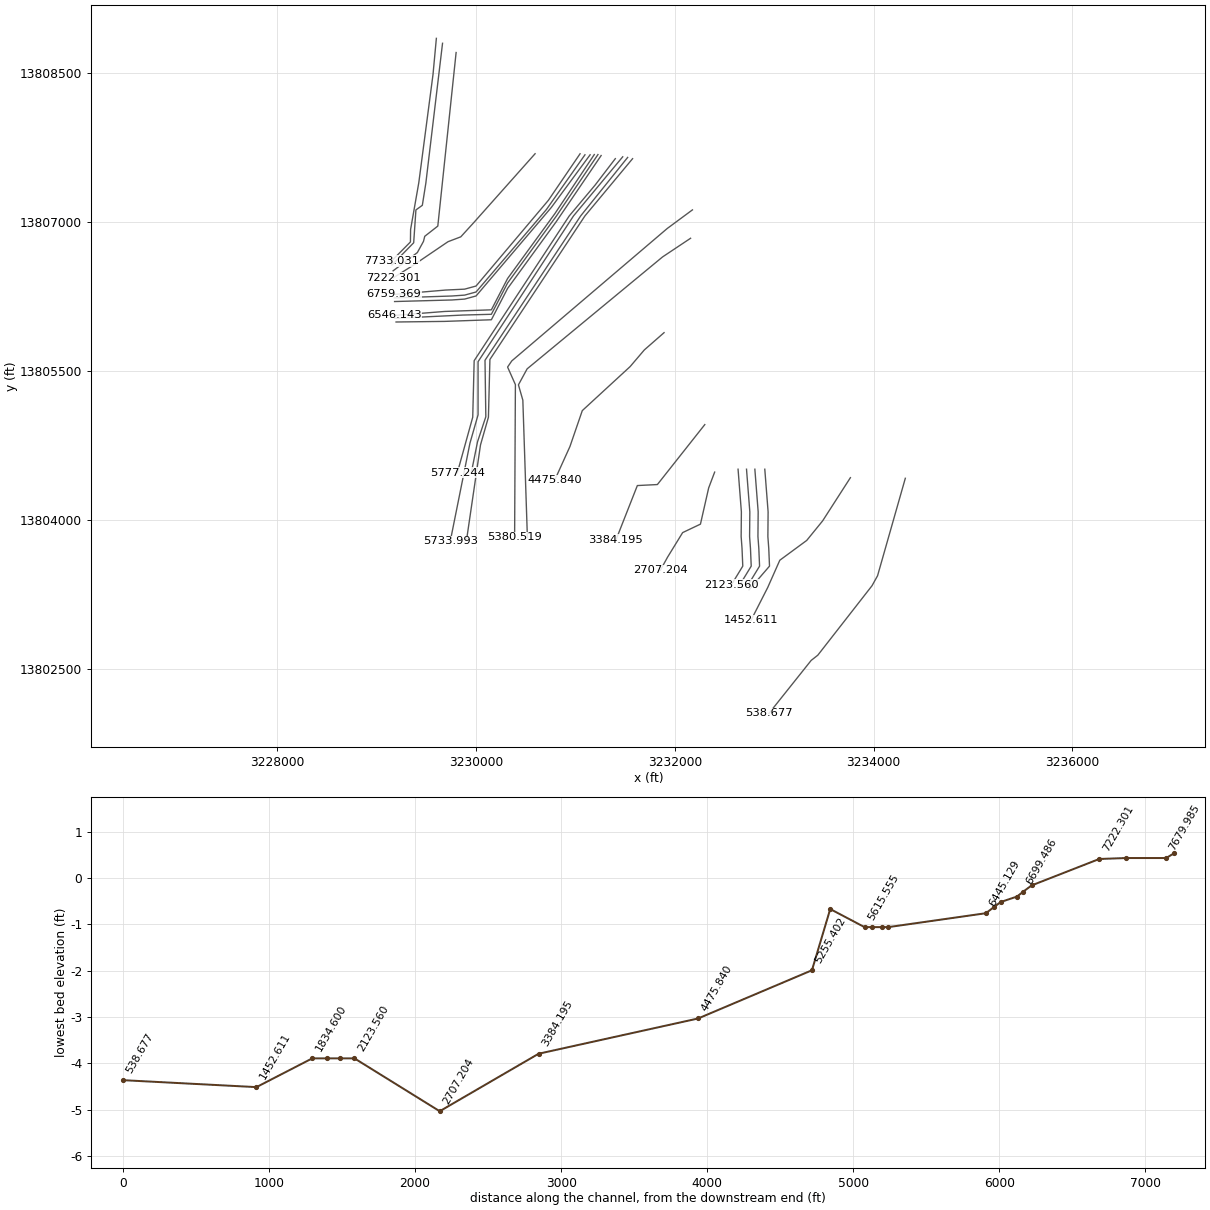
HEC-RAS study F216-00-00.prj: F216-00-00

--- F216-00-00.g03 (geometry) --- (continued)

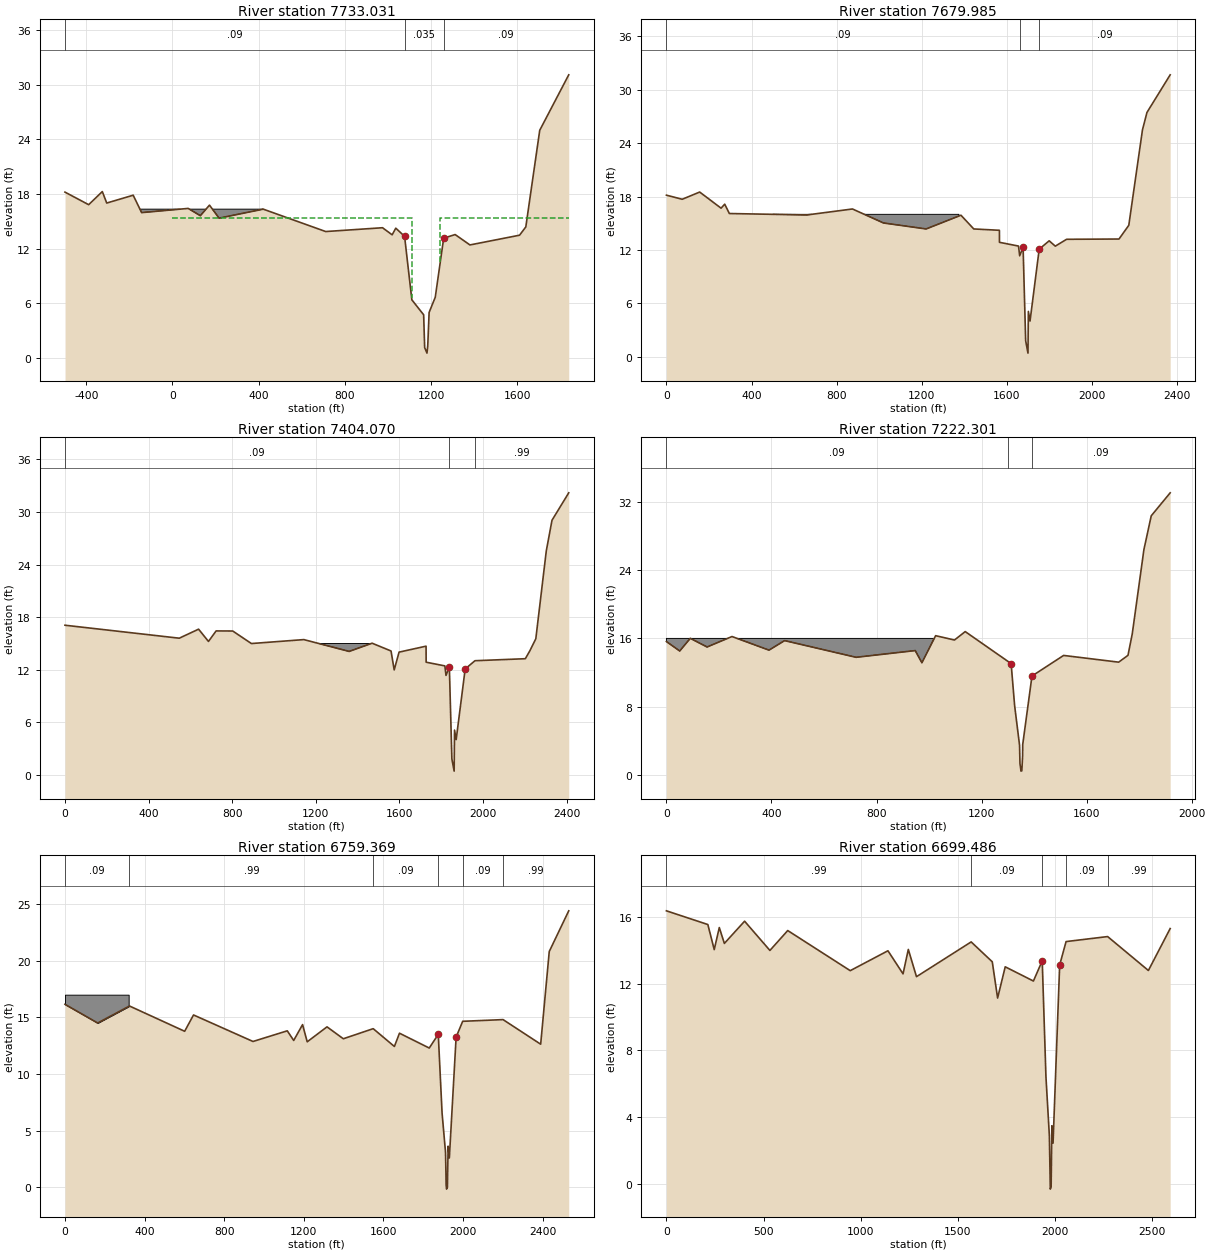
Type RM Length L Ch R = 1 ,7733.031,88.43,53.05,82.46
BEGIN DESCRIPTION:
Copy of 471s6u:  XS 2/4.
Bank Station offset =      3312
LOB block b/c water will not get in area
END DESCRIPTION:
XS GIS Cut Line= 6
     3229599.349    13808845.637     3229565.275    13808479.673
     3229422.469     13807392.61     3229339.925    13806921.884
     3229338.208    13806796.573     3229147.926    13806604.237
#Sta/Elev= 30
    -499   18.21 -389.01   16.83 -325.71   18.27 -305.22   17.01 -182.41   17.87
 -143.23   15.96   72.77   16.42  129.28   15.62  171.71   16.78  216.25   15.35
  421.19   16.34  711.14   13.88   974.8    14.3  1019.5   13.52 1036.35   14.25
 1077.12   13.36 1110.99    6.38 1165.71    4.74 1170.37    1.14 1181.12     .53
 1184.71    1.35 1191.08       5 1219.61    6.67  1258.7   13.15 1311.82   13.55
 1380.57   12.41 1610.79   13.48 1639.84   14.39 1704.47      25 1839.07   31.09
#Mann= 3 ,-1 , 0
    -499     .09       0 1077.12    .035       0  1258.7     .09       0
#XS Ineff= 2 , 0
       0    1110    15.4    1243       0    15.4
Permanent Ineff=
       F       F
#Block Obstruct= 2 , 0
    -499     421   16.34            -499
Bank Sta=1077.12,1258.7
XS Rating Curve= 0
Exp/Cntr=.5,.3

Type RM Length L Ch R = 1 ,7679.985,267.98,275.92,202.67
BEGIN DESCRIPTION:
471s5d:  XS 1.9/4
Bank Station offset =      3300
LOB block b/c water will not get in area
END DESCRIPTION:
XS GIS Cut Line= 6
     3229661.444    13808795.961     3229493.469     13807388.61
     3229458.037    13807165.122     3229393.535    13807118.788
        3229371.    13806788.256     3229151.862    13806564.712
#Sta/Elev= 30
       0   18.15    74.2   17.69  156.37    18.5  256.96   16.69  274.08   17.14
  295.86   16.09  659.98   15.93  874.62    16.6 1020.22   15.03 1220.94   14.36
 1384.42    15.9 1444.71   14.36 1565.26   14.21 1565.55   12.86 1655.07   12.44
 1660.43   11.35 1676.53   12.32 1688.64    1.82 1699.53     .43  1701.3    5.11
  1709.2    4.03 1752.24   12.09 1799.16   13.03 1827.92   12.43 1881.08    13.2
 2127.32   13.23 2173.44   14.77 2237.73   25.48 2258.82   27.43 2367.98   31.65
#Mann= 3 ,-1 , 0
       0     .09       0 1660.43    .035       0 1752.24     .09       0
#Block Obstruct= 2 , 0
       0    1375      16               0
Bank Sta=1676.53,1752.24
XS Rating Curve= 0
Exp/Cntr=.3,.1

Type RM Length L Ch R = 1 ,7404.070,184.54,181.77,166.2
BEGIN DESCRIPTION:
Copy of 471s5d:  XS 1/4.
Bank Station offset =      3138
END DESCRIPTION:
XS GIS Cut Line= 6
     3229798.053    13808702.818     3229613.762    13806956.263
     3229482.246    13806853.314     3229469.663    13806802.226
     3229407.805    13806689.543     3229164.066    13806506.133
#Sta/Elev= 30
       0   17.08  546.58    15.6  639.08   16.63  686.37   15.23  722.92   16.43
  802.39   16.42  891.72   14.99 1142.66   15.44 1359.42   14.09 1469.06   15.03
 1559.65   14.14 1574.74   11.98 1598.02   14.01 1727.17   14.69 1727.56   12.86
 1817.08   12.44 1822.44   11.35 1838.54   12.32 1850.65    1.82 1861.54     .43
 1863.31    5.11 1871.21    4.03 1914.25   12.09 1961.17   13.03 2202.03   13.26
 2224.24   14.19 2252.17   15.54 2302.21   25.56 2329.54   29.06 2409.61   32.19
#Mann= 3 ,-1 , 0
       0     .09       0 1838.54    .035       0 1961.17     .99       0
#Block Obstruct= 2 , 0
       0    1470      15               0
Bank Sta=1838.54,1914.25
XS Rating Curve= 0
Exp/Cntr=.3,.1

Type RM Length L Ch R = 1 ,7222.301,494.73,462.93,429.32
BEGIN DESCRIPTION:
471v8
Bank Station offset =      3650
END DESCRIPTION:
XS GIS Cut Line= 6
     3230592.872    13807684.457      3229973.35    13806988.671
     3229844.927    13806848.018     3229716.505    13806799.095
     3229374.044    13806566.711     3229167.003    13806436.441
#Sta/Elev= 30
       0   15.63   50.64   14.52   90.91   16.01  154.73   14.99  249.66   16.22
  390.56   14.62  450.04   15.74  722.07   13.78  947.19   14.57  972.68   13.14
 1025.01   16.32 1096.74   15.81 1137.64    16.8 1300.83   13.29  1312.5   13.01
 1325.75     8.1 1344.52    3.45 1346.04     1.3    1350     .41 1353.16     .45
 1356.09    2.17 1356.54    3.54  1391.8   11.58 1512.25      14 1721.83   13.21
 1757.33   14.01 1773.58   16.53 1818.01   26.44 1845.88    30.4    1918    33.1
#Mann= 3 ,-1 , 0
       0     .09       0 1300.83    .045       0  1391.8     .09       0
#Block Obstruct= 2 , 0
       0    1030      16               0
Bank Sta=1312.5,1391.8
XS Rating Curve= 0
Exp/Cntr=.3,.1

Type RM Length L Ch R = 1 ,6759.369,60.65,59.88,60.02
BEGIN DESCRIPTION:
Copy of 471s4u:  XS 4/4.
Bank Station offset =      3083
END DESCRIPTION:
XS GIS Cut Line= 6
       3231045.5    13807684.053     3230726.738     13807215.83
     3229998.712    13806352.953     3229883.509    13806321.534
     3229693.498    13806312.557     3229169.126    13806267.984
#Sta/Elev= 30
       0   16.15  164.29    14.5  324.21      16  601.41   13.77  645.95   15.21
  944.81   12.87 1117.02   13.81 1149.29   12.96 1193.88   14.36 1217.19   12.84
  1316.7   14.16 1398.65   13.11 1548.81      14 1655.31   12.43 1680.97    13.6
 1830.46   12.29 1875.77    13.5 1894.89    6.56 1912.42    3.05 1915.28     .21
 1917.36    -.16 1921.59    -.01 1925.35    3.63 1931.44    2.59  1965.5   13.25
 1998.44   14.65 2201.29    14.8 2390.38   12.63 2433.49   20.81  2531.4    24.4
#Mann= 6 ,-1 , 0
       0     .09       0  324.21     .99       0 1548.81     .09       0
 1875.77    .045       0 1998.44     .09       0 2201.29     .99       0
#Block Obstruct= 2 , 0
       0     320      17               0
Bank Sta=1875.77,1965.5
XS Rating Curve= 0
Exp/Cntr=.5,.3

Type RM Length L Ch R = 1 ,6699.486,40.43,39.92,40.03
BEGIN DESCRIPTION:
471s4u:  XS 3.5/4.
Bank Station offset =      3025
END DESCRIPTION:
XS GIS Cut Line= 6
     3231094.733    13807673.658     3230706.275    13807122.422
     3229998.712    13806292.953     3229883.509    13806261.534
     3229753.344    13806252.557     3229176.479    13806233.673
#Sta/Elev= 30
       0   16.35  213.15   15.53  245.97   14.03  272.01   15.35  298.05    14.4
   402.2   15.73   532.4   13.98  624.14   15.17  945.67   12.77 1139.67   13.96
 1217.32   12.58  1244.5   14.04 1286.49   12.41 1567.77   14.49 1676.45    13.3
 1703.82   11.13 1743.03      13 1888.11   12.15 1933.42   13.36 1952.54    6.42
 1970.07    2.91 1975.01     -.3 1979.24    -.15    1983    3.49 1989.09    2.45
 2023.15   13.11 2056.09   14.51 2269.93   14.81 2479.56   12.78 2591.72   15.29
#Mann= 5 ,-1 , 0
       0     .99       0 1567.77     .09       0 1933.42    .045       0
 2056.09     .09       0 2269.93     .99       0
#Block Obstruct= 2 , 0
       0                    2590       0      17
Bank Sta=1933.42,2023.15
XS Rating Curve= 0
Exp/Cntr=.5,.3

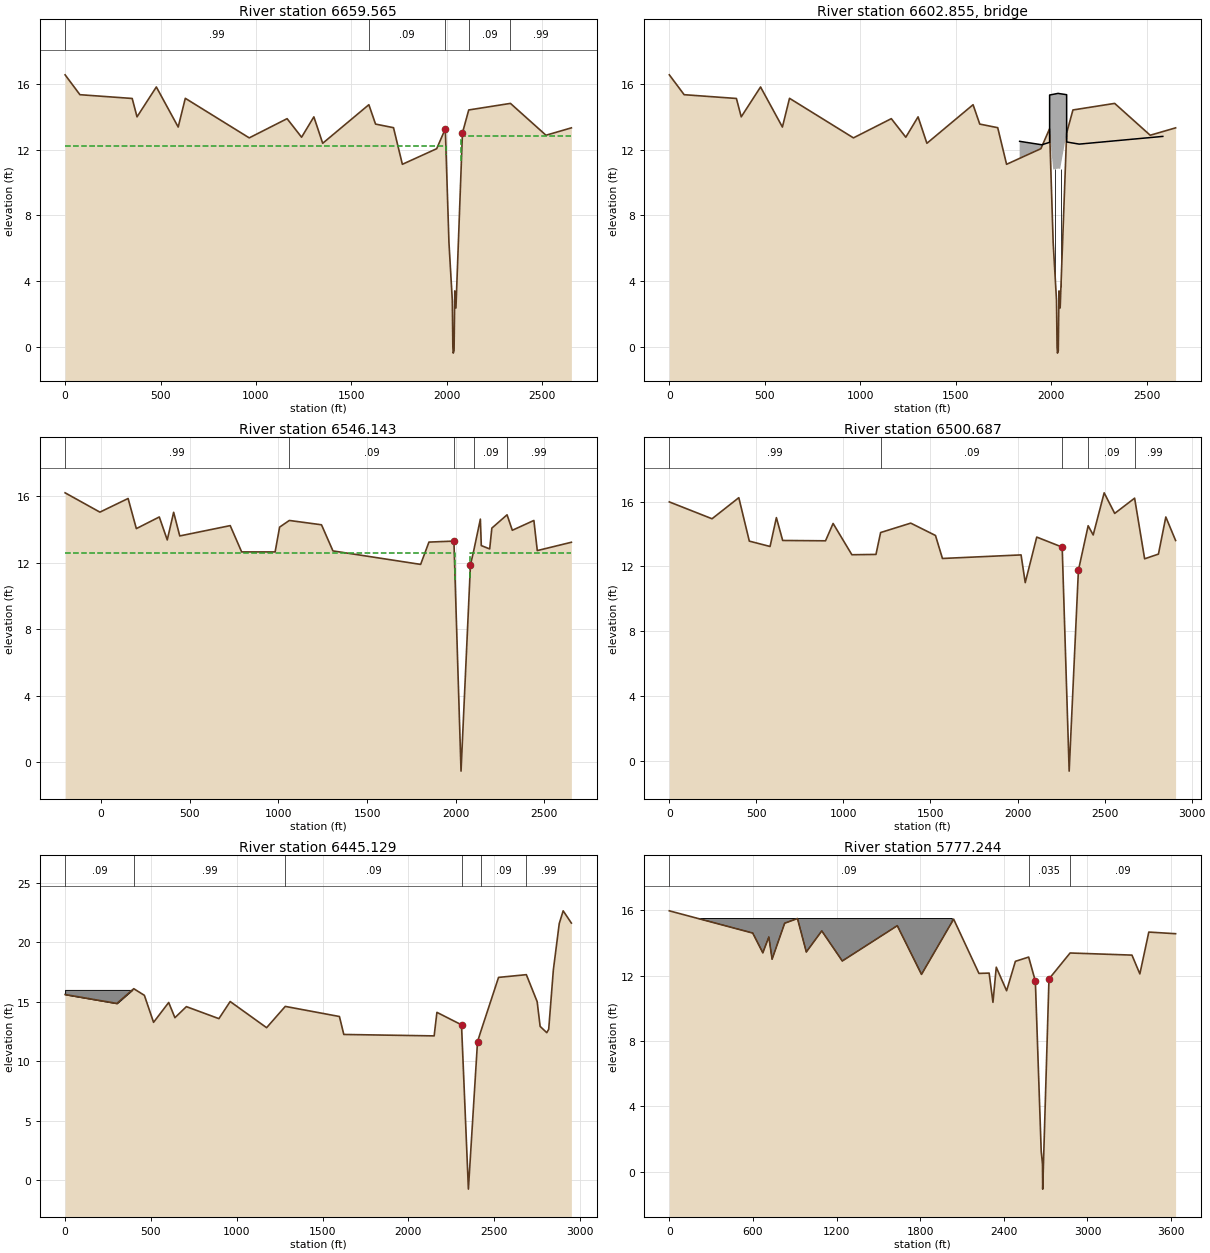
Type RM Length L Ch R = 1 ,6659.565,115.29,113.42,113
BEGIN DESCRIPTION:
Copy of 471s4u:  XS 3/4.
Bank Station offset =      2967
ROB not blocked b/c there will be flow.  A lateral weir will not be used b/c DEC has calculated flows.  Right most side of XS represents the limits of downstream conveyance.
END DESCRIPTION:
XS GIS Cut Line= 6
     3231146.534    13807673.658      3230755.62    13807143.121
     3229998.712    13806252.953     3229883.509    13806221.534
     3229753.344    13806212.557      3229178.93    13806196.911
#Sta/Elev= 30
       0   16.55   77.65   15.34  351.47   15.11  376.75   13.99   477.9   15.81
   592.4   13.37  629.67   15.12  964.51   12.71 1162.85   13.88 1238.76   12.75
 1303.04   13.99 1349.31   12.38 1591.15   14.73 1626.18   13.55 1720.29   13.33
 1766.66    11.1 1946.34   12.05 1991.65   13.26 2010.77    6.32  2028.3    2.81
 2031.16    -.03 2033.24     -.4 2037.47    -.25 2041.23    3.39 2047.32    2.35
 2081.38   13.01 2114.32   14.41 2332.87   14.81 2518.97   12.87    2652   13.32
#Mann= 5 ,-1 , 0
       0     .99       0 1591.15     .09       0 1991.65    .035       0
 2114.32     .09       0 2332.87     .99       0
#XS Ineff= 2 , 0
       0    1996    12.2    2076       0    12.8
Permanent Ineff=
       F       F
#Block Obstruct= 2 , 0
       0                    2652       0    15.6
Bank Sta=1991.65,2081.38
XS Rating Curve= 0
Exp/Cntr=.5,.3

Type RM Length L Ch R = 3 ,6602.855,,,
BEGIN DESCRIPTION:
(North & South) Fairmont Parkway, 471s3
& 471s4.
Six sections around this structure since north and south were combined.
 Top of deck/roadway extensions assumed based on aerial photos and GIS tin elevations.
High cord includes side rails. i.e. It is not the top of road.
END DESCRIPTION:
Bridge Culvert--1,0,-1,-1, 0
Deck Dist Width WeirC Skew NumUp NumDn MinLoCord MaxHiCord MaxSubmerge Is_Ogee
10,93,2.6,0, 9, 9, 12.29, , .95, 0, 0,3.92,,
    1835 1951.44  1992.1 1992.12    2036 2081.33  2081.4 2147.08    2585
    12.5   12.29   12.44   15.32   15.42   15.34   12.46   12.33    12.8
       0       0       0   10.74   10.84   10.76       0       0       0
    1572 1949.95 1992.47  1992.5    2036 2082.39  2082.4 2125.76    2583
      13   12.41   12.48   15.36   15.43   15.31   12.43   12.32    12.8
               0       0   10.78   10.85   10.73       0       0       0
Pier Skew, UpSta & Num, DnSta & Num=  ,2021.17, 4 ,2022.65, 4 , 3 , 3 , 0 ,0,
    1.35    1.35       2       2
    1.92    8.31    8.31   10.85
    1.35    1.35       2       2
    1.92    8.31    8.31   10.85
Pier Skew, UpSta & Num, DnSta & Num=  ,2051.35, 4 ,2052.69, 4 , 3 , 3 , 0 ,0,
    1.35    1.35       2       2
    2.26    8.31    8.31   10.85
    1.35    1.35       2       2
    2.26    8.31    8.31   10.85
BR Coef=-1 , 0 , 0 ,, 0 ,,,.8,0,,0,
WSPro=,,,, 1 ,,,, 0 ,,,, 0 ,,,,-1 ,-1 ,-1 , 0 , 0 , 0 , 0 , 0
BC Design=,, 0 ,, 0 ,,,,,,

Type RM Length L Ch R = 1 ,6546.143,45.4,45.46,45.14
BEGIN DESCRIPTION:
Copy of 471s3d:  XS 2/4.
Bank Station offset =      2767
ROB not blocked b/c there will be flow.  A lateral weir will not be used b/c DEC has calculated flows.  Right most side of XS represents the limits of downstream conveyance.
END DESCRIPTION:
XS GIS Cut Line= 6
     3231188.468    13807676.125     3230792.095    13807081.756
     3230315.811     13806428.25     3230152.816     13806113.53
     3229683.025    13806097.073     3229176.479    13806057.215
#Sta/Elev= 30
    -203    16.2   -6.69   15.04  152.37   15.86  198.82   14.05  328.32   14.75
  373.21   13.37  409.27   15.03   443.7   13.61   728.3   14.23  792.88   12.65
  981.65   12.65 1006.98   14.14 1061.83   14.54 1243.22   14.28 1307.78   12.71
 1802.36    11.9 1849.32   13.24 1990.18    13.3 2030.28    -.52  2083.4   11.87
    2101   12.68 2139.36   14.62 2144.59   13.03 2191.92   12.83 2204.09   14.08
 2289.87   14.88  2319.6   13.95 2441.17   14.54 2460.36   12.73  2652.7   13.23
#Mann= 5 ,-1 , 0
    -203     .99       0 1061.83     .09       0 1990.18    .035       0
    2101     .09       0 2289.87     .99       0
#XS Ineff= 2 , 0
    -203    1997    12.6    2080    -203    12.6
Permanent Ineff=
       F       F
#Block Obstruct= 2 , 0
       0                  2652.7       0    15.6
Bank Sta=1990.18,2083.4
XS Rating Curve= 0
Exp/Cntr=.5,.3

Type RM Length L Ch R = 1 ,6500.687,55.08,55.56,55.12
BEGIN DESCRIPTION:
471s3d:  XS 1.5/4.
Bank Station offset =      2703
END DESCRIPTION:
XS GIS Cut Line= 6
     3231225.469    13807676.125        3230806.    13807055.835
     3230315.811     13806383.25     3230152.816     13806068.53
     3229870.043    13806061.049      3229181.38    13806027.806
#Sta/Elev= 30
       0   15.98  245.32   14.94  399.17   16.24  459.53   13.56  578.71   13.23
  614.93   15.01  651.14    13.6  897.25   13.58  940.71   14.65 1048.57   12.72
 1186.97   12.74 1213.63   14.09 1386.57   14.67 1528.65   13.91 1568.78   12.49
 2020.29   12.71 2044.27      11 2110.32   13.81 2256.48   13.19 2296.58    -.63
  2349.7   11.76 2405.66   14.51 2434.55   13.94  2497.6   16.54 2558.16   15.27
 2672.47   16.21 2730.02   12.47 2809.35   12.76 2851.71   15.05 2907.83    13.6
#Mann= 5 ,-1 , 0
       0     .99       0 1213.63     .09       0 2256.48    .045       0
 2405.66     .09       0 2672.47     .99       0
#Block Obstruct= 2 , 0
       0                    2850       0      15
Bank Sta=2256.48,2349.7
XS Rating Curve= 0
Exp/Cntr=.3,.1

Type RM Length L Ch R = 1 ,6445.129,581.44,667.89,751.11
BEGIN DESCRIPTION:
Copy of 471s3d:  XS 1/4.
Bank Station offset =      2650
END DESCRIPTION:
XS GIS Cut Line= 6
     3231257.536    13807666.258     3230804.777    13806999.156
     3230315.811     13806328.25     3230152.816     13806013.53
     3229683.025    13805997.073     3229193.634    13805991.044
#Sta/Elev= 30
       0   15.61  301.81   14.86  400.17    16.1  462.08   15.54   515.5   13.27
   603.7   14.94  639.96   13.66  706.72   14.59  896.27   13.58  961.98   15.02
 1174.26   12.82 1283.06   14.61 1598.66   13.76 1624.13   12.25 2150.66   12.13
 2166.78   14.11 2310.14   13.06 2350.24    -.76 2403.36   11.63 2420.96   12.44
 2525.93   17.05 2688.03   17.28 2750.95   15.01 2768.26   12.93 2807.02    12.4
 2818.24   12.69 2845.35   17.68 2879.66   21.58 2902.55   22.65 2950.37   21.62
#Mann= 6 ,-1 , 0
       0     .09       0  400.17     .99       0 1283.06     .09       0
 2310.14    .045       0 2420.96     .09       0 2688.03     .99       0
#Block Obstruct= 2 , 0
       0     400      16               0      16
Bank Sta=2310.14,2403.36
XS Rating Curve= 0
Exp/Cntr=.3,.1

Type RM Length L Ch R = 1 ,5777.244,45.62,43.25,44.99
BEGIN DESCRIPTION:
471s2u:  XS 4/4
Bank Station offset =      2321
END DESCRIPTION:
XS GIS Cut Line= 6
      3231400.11    13807634.781     3231196.131    13807367.985
     3230936.194    13807058.197     3229979.731    13805601.617
     3229965.211    13805032.923     3229810.472    13804474.135
#Sta/Elev= 30
       0   15.97  598.37   14.61   670.9    13.4  714.02   14.37  737.35   13.01
   827.5   15.21   919.4    15.5  982.81   13.45  1093.8   14.74 1240.98    12.9
 1635.47   15.06 1809.18   12.08 2039.87   15.46 2221.38   12.14 2294.55   12.16
 2321.88   10.37 2345.61   12.52 2419.81   11.08 2482.77   12.88    2578   13.14
 2626.01   11.67 2667.95    1.27 2677.21     .48 2678.76   -1.06 2723.75    11.8
 2875.19   13.39 3319.11   13.26 3375.73   12.11 3440.01   14.67  3632.1   14.57
#Mann= 3 ,-1 , 0
       0     .09       0    2578    .035       0 2875.19     .09       0
#Block Obstruct= 2 , 0
       0    2030    15.5    3500       0      16
Bank Sta=2626.01,2723.75
XS Rating Curve= 0
Exp/Cntr=.5,.3

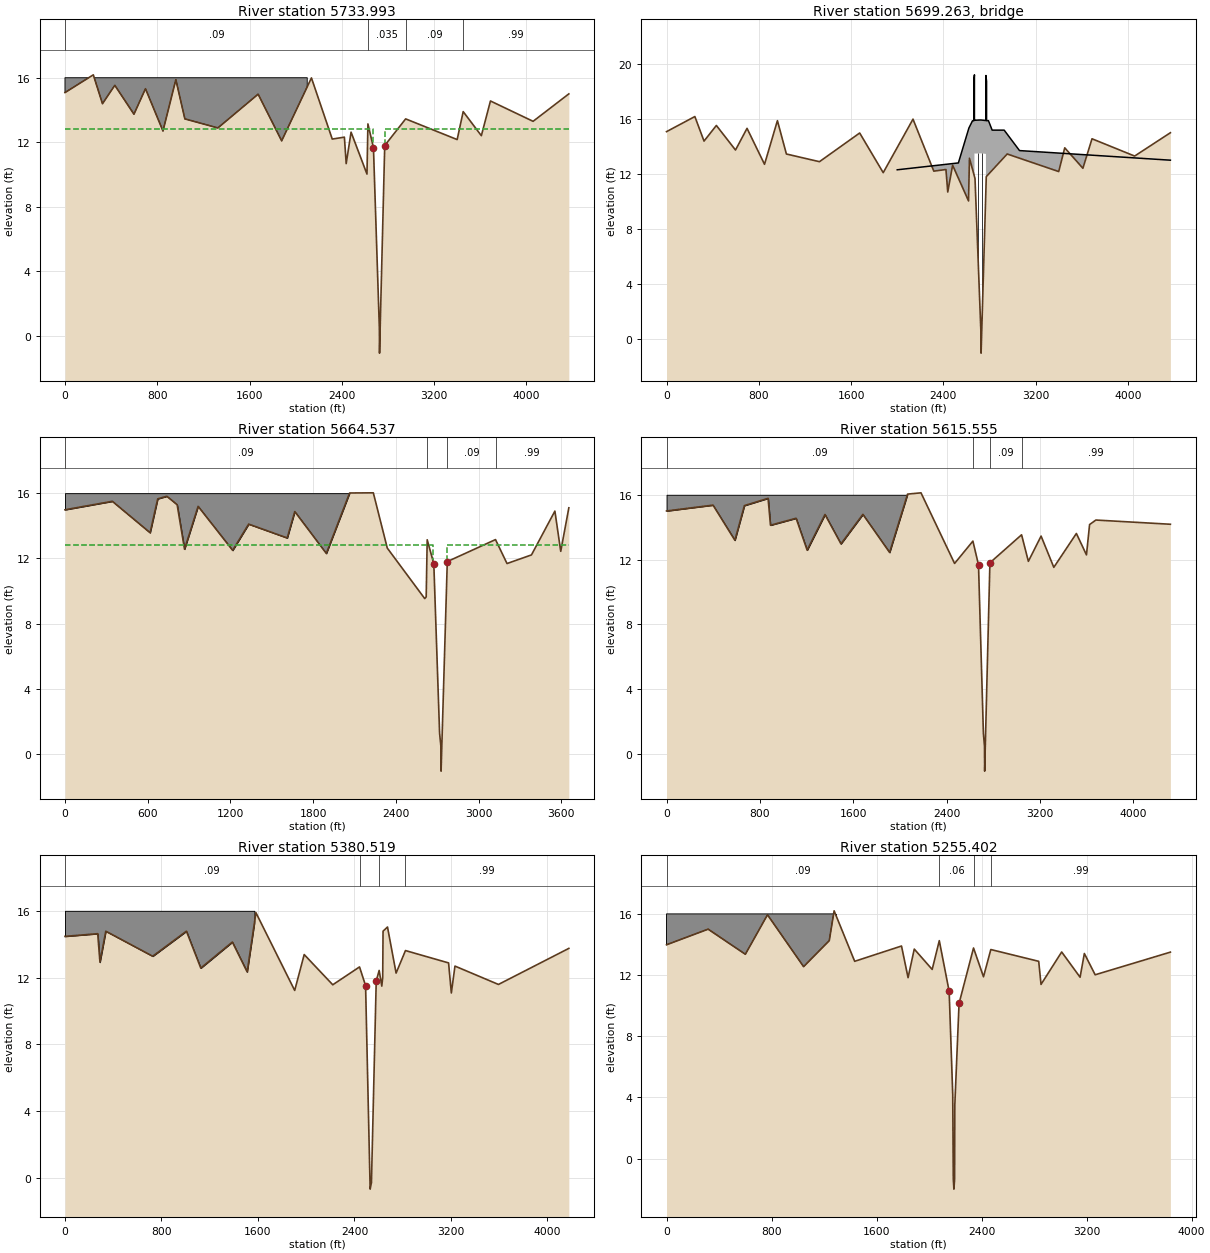
Type RM Length L Ch R = 1 ,5733.993,66.13,69.46,69.71
BEGIN DESCRIPTION:
Copy of 471s2u:  XS 3/4.
Bank Station offset =      2273
XS extended on ROB
END DESCRIPTION:
XS GIS Cut Line= 6
     3231474.624    13807653.409     3230979.194    13807058.197
     3230018.828    13805591.329     3230018.828    13805056.318
     3229937.196    13804771.342 3229738.869522813803783.0698836
#Sta/Elev= 30
       0   15.08   245.6   16.18  325.05   14.39  431.99   15.53  597.95   13.74
  697.85   15.32  849.55    12.7  961.21   15.88 1039.13   13.45 1325.59   12.89
 1674.37   14.98 1878.48   12.09 2136.63   15.99 2317.01    12.2 2422.21   12.32
 2437.86   10.68 2480.11   12.63 2618.04   10.03 2626.15   13.14 2674.16   11.67
 2725.36     .48 2726.91   -1.06  2771.9    11.8 2953.27   13.45 3399.89   12.17
 3452.12    13.9 3609.51   12.41 3688.49   14.56    4058    13.3    4368      15
#Mann= 4 ,-1 , 0
       0     .09       0 2626.15    .035       0 2953.27     .09       0
 3452.12     .99       0
#XS Ineff= 2 , 0
       0    2669    12.8    2775       0    12.8
Permanent Ineff=
       F       F
#Block Obstruct= 2 , 0
       0    2100      16    4368       0      16
Bank Sta=2674.16,2771.9
XS Rating Curve= 0
Exp/Cntr=.5,.3

Type RM Length L Ch R = 3 ,5699.263,,,
BEGIN DESCRIPTION:
(South) 8th St., 471s2, concrete bridge
Bridge opening 100 ft
Top of deck/roadway extensions assumed based on aerial photos and GIS tin elevations.
END DESCRIPTION:
Bridge Culvert--1,0,-1,-1, 0
Deck Dist Width WeirC Skew NumUp NumDn MinLoCord MaxHiCord MaxSubmerge Is_Ogee
17.7,34,2.6,0, 19, 19, 12.3, , .95, 0, 0,0,,
    2000    2530 2621.01 2652.27 2663.49 2663.49 2669.28 2669.28 2671.61    2723
 2768.67 2768.67 2774.32 2774.32  2790.7 2822.83    2927    3060    4368
    12.3    12.8   15.34   15.87   15.87   18.83   19.22   15.91   15.91   15.93
   15.89   19.17   18.76   15.88   15.88   15.19   15.19    13.7      13
       0       0       0       0       0       0       0   13.48   13.48    13.5
   13.46       0       0       0       0       0       0       0
    2000    2515 2623.01 2654.27 2665.49 2665.49 2671.28 2671.28 2673.61    2725
 2770.67 2770.67 2776.32 2776.32  2792.7 2824.83    2929    3060    3655
    12.3    12.8   15.34   15.87   15.87   18.83   19.22   15.91   15.91   15.93
   15.89   19.17   18.76   15.88   15.88   15.19   15.19    13.7      13
       0       0       0       0       0       0       0   13.48   13.48    13.5
   13.46       0       0       0       0       0       0       0
Pier Skew, UpSta & Num, DnSta & Num=  ,2702.8, 4 ,2704.8, 4 , 3 , 3 , 0 ,0,
    1.35    1.35    2.35    2.35
    2.47   11.57   11.57   15.91
    1.35    1.35    2.35    2.35
    2.47   11.57   11.57   15.91
Pier Skew, UpSta & Num, DnSta & Num=  ,2735.91, 4 ,2737.91, 4 , 3 , 3 , 0 ,0,
    1.35    1.35    2.35    2.35
    1.65    11.5    11.5   15.93
    1.35    1.35    2.35    2.35
    1.65    11.5    11.5   15.93
BR Coef=-1 , 0 , 0 ,, 0 ,,,.8,0,,0,
WSPro=,,,, 1 ,,,, 0 ,,,, 0 ,,,,-1 ,-1 ,-1 , 0 , 0 , 0 , 0 , 0
BC Design=,, 0 ,, 0 ,,,,,,

Type RM Length L Ch R = 1 ,5664.537,52.41,48.98,44.35
BEGIN DESCRIPTION:
Copy of 471s2u:  XS2/4.
Bank Station offset =      2271
END DESCRIPTION:
XS GIS Cut Line= 6
       3231524.3      13807647.2     3231051.194    13807058.197
     3230088.791    13805605.733     3230097.022    13805037.799
     3230013.458    13804785.249 3229949.858004513804469.1240945
#Sta/Elev= 30
       0   14.98  343.69    15.5  617.52   13.57  672.77   15.65  739.06   15.81
  813.67   15.29  867.27   12.56  965.94   15.19 1216.48   12.49 1332.65    14.1
 1612.33   13.25 1667.13   14.87 1895.95    12.3 2065.03   16.01 2236.93   16.02
  2338.2   12.63 2609.77    9.53 2620.51    9.63 2627.78   13.14 2675.79   11.67
 2717.73    1.27 2726.99     .48 2728.54   -1.06 2773.53    11.8 3123.33   13.15
 3206.91   11.68  3384.3   12.21 3554.18    14.9 3596.62   12.43 3655.39    15.1
#Mann= 4 ,-1 , 0
       0     .09       0 2627.78    .035       0 2773.53     .09       0
 3123.33     .99       0
#XS Ineff= 2 , 0
       0    2669    12.8    2775       0    12.8
Permanent Ineff=
       F       F
#Block Obstruct= 2 , 0
       0    2100      16               0
Bank Sta=2675.79,2773.53
XS Rating Curve= 0
Exp/Cntr=.5,.3

Type RM Length L Ch R = 1 ,5615.555,210.71,235.04,263.35
BEGIN DESCRIPTION:
Copy of 471s2u:  XS 1/4.  .
Bank Station offset =      2274
Extended cross section to edge of watershed on ROB
END DESCRIPTION:
XS GIS Cut Line= 6
     3231573.976    13807634.781     3231094.194    13807058.197
     3230138.176    13805613.964     3230123.211    13805032.923
     3230043.521    13804754.397 3229903.499117513803800.2139391
#Sta/Elev= 30
       0      15  398.43   15.36  585.93   13.19  667.16   15.33  870.31   15.78
  890.81   14.12 1110.49   14.55 1205.17   12.58 1358.12   14.78 1494.97   12.97
 1682.83   14.79 1911.68   12.44 2065.64   16.04 2180.69   16.12 2468.54   11.76
 2625.56   13.14 2673.57   11.67 2715.51    1.27 2724.77     .48 2726.32   -1.06
 2771.31    11.8 3042.66   13.53 3100.85   11.89 3209.91   13.45 3318.97   11.52
 3512.42   13.61 3598.79   12.29 3625.47   14.16 3679.19   14.44    4318   14.18
#Mann= 4 ,-1 , 0
       0     .09       0 2625.56    .035       0 2771.31     .09       0
 3042.66     .99       0
#Block Obstruct= 2 , 0
       0    2100      16               0
Bank Sta=2673.57,2771.31
XS Rating Curve= 0
Exp/Cntr=.3,.1

Type RM Length L Ch R = 1 ,5380.519,166.65,125.12,86.77
BEGIN DESCRIPTION:
471v7
Bank Station offset =      2470
Cross section extended to edge of watershed on ROB
END DESCRIPTION:
XS GIS Cut Line= 6
       3232176.3     13807119.39     3231922.644    13806932.007
     3230358.164    13805599.335     3230316.068    13805537.595
     3230394.647    13805360.793 3230386.705284713803822.6576305
#Sta/Elev= 30
       0   14.47  271.35   14.63     290   12.92   338.3   14.78  727.38   13.28
 1006.72   14.78 1125.87   12.57 1387.55   14.13 1510.23   12.34 1582.96   15.89
 1904.32   11.23 1983.14   13.38 2219.97   11.57 2441.74   12.64 2492.02   11.52
 2529.86    -.67 2540.58    -.28 2580.22    11.8 2604.57   12.43  2626.4   11.49
 2633.97   12.02 2636.78   14.78 2673.68   15.03 2744.99   12.27 2822.61   13.62
 3180.03   12.88 3202.92   11.08 3232.92   12.69 3593.49   11.59    4177   13.75
#Mann= 4 ,-1 , 0
       0     .09       0 2441.74     .06       0 2604.57     .09       0
 2822.61     .99       0
#Block Obstruct= 2 , 0
       0    1570      16    4177       0      16
Bank Sta=2492.02,2580.22
XS Rating Curve= 0
Exp/Cntr=.3,.1

Type RM Length L Ch R = 1 ,5255.402,792.23,779.56,769.23
BEGIN DESCRIPTION:
471v6
Bank Station offset =      2811
Extended cross section to edge of watershed on ROB
END DESCRIPTION:
XS GIS Cut Line= 6
     3232157.671    13806833.752     3231875.623     13806645.86
     3230512.797    13805519.649     3230425.166    13805358.693
     3230469.471    13805204.475 3230515.4501906 13803820.189287
#Sta/Elev= 30
       0   13.98  316.85      15  600.43   13.36  769.04   15.94 1044.09   12.55
 1239.49   14.25 1276.54    16.2 1433.14    12.9 1789.84    13.9 1839.81   11.83
 1886.98    13.7 2023.52   12.37  2077.7   14.25 2152.76   10.94 2180.07    4.19
 2184.29   -1.29 2188.86   -1.99 2194.32   -1.35  2195.9    3.51 2228.22   10.15
 2338.42   13.77 2414.36   11.89 2470.23   13.67 2834.94    12.9 2852.59   11.39
 3009.93   13.51 3150.07   11.86 3182.68   13.41 3264.92   12.02    3838    13.5
#Mann= 4 ,-1 , 0
       0     .09       0  2077.7     .06       0 2338.42     .09       0
 2470.23     .99       0
#Block Obstruct= 2 , 0
       0    1290      16    3838       0      16
Bank Sta=2152.76,2228.22
XS Rating Curve= 0
Exp/Cntr=.3,.1

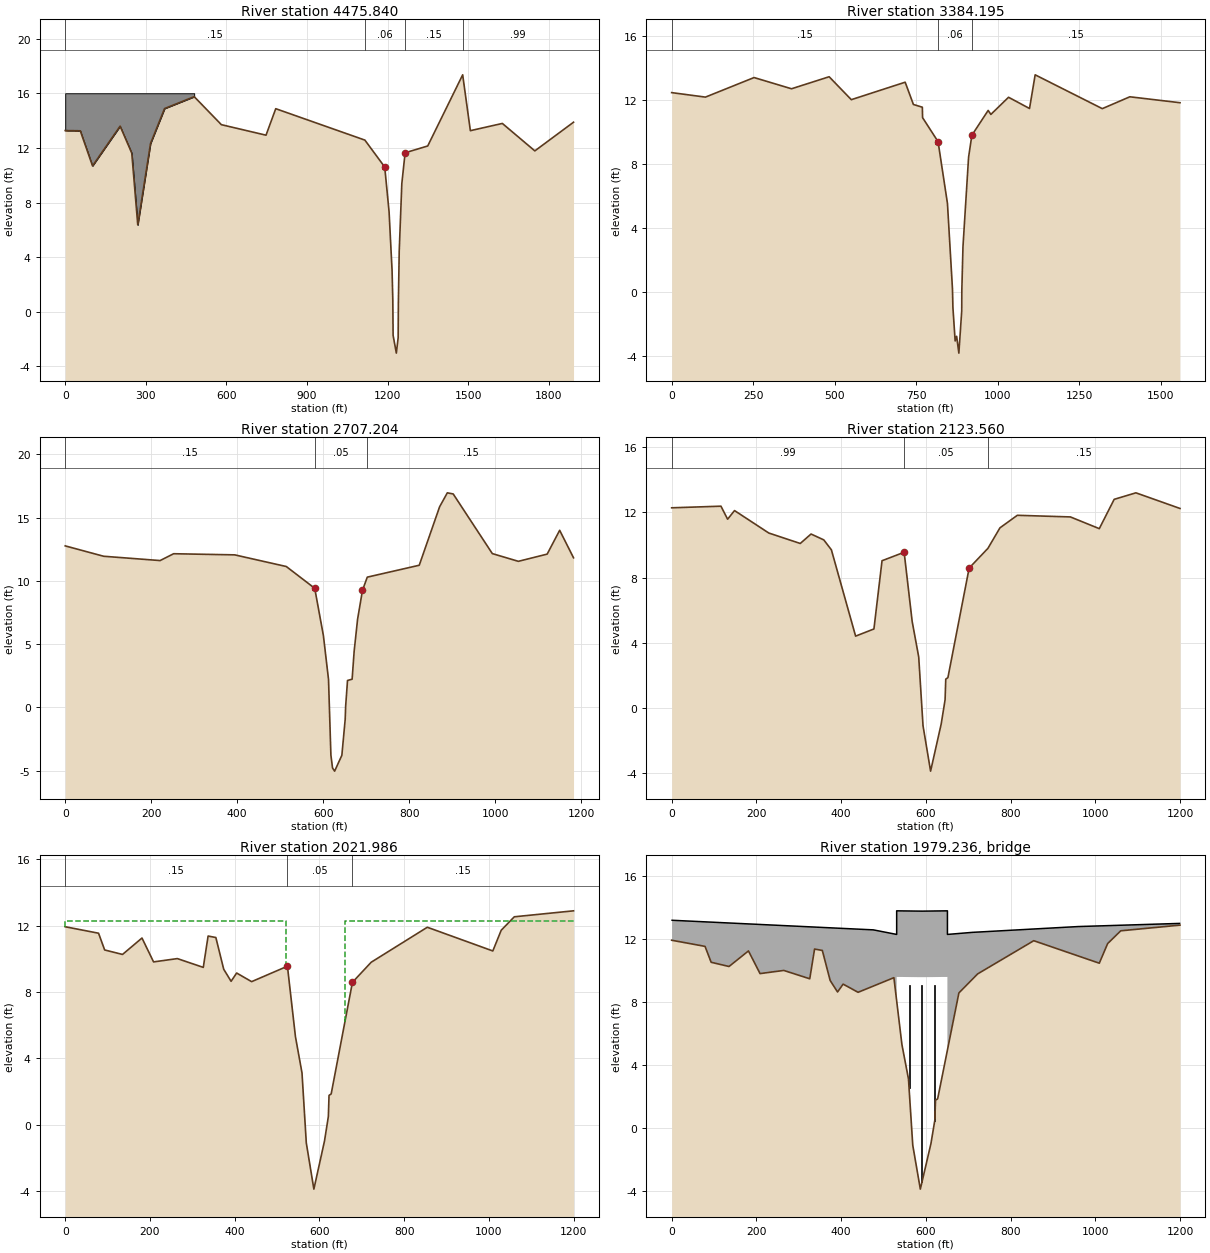
Type RM Length L Ch R = 1 ,4475.840,1127.8,1091.64,1062.82
BEGIN DESCRIPTION:
471v5
Bank Station offset =      3768
END DESCRIPTION:
XS GIS Cut Line= 6
     3231890.662    13805883.696     3231691.957    13805709.829
     3231549.138    13805542.172     3231067.803    13805099.207
       3230943.5    13804737.846  3230790.36865213804399.7736148
#Sta/Elev= 30
       0   13.27   56.12   13.25  101.68   10.68   204.3   13.59  247.67   11.62
  270.06    6.36  317.54   12.32  369.83   14.88  480.11   15.75  581.14    13.7
  747.35   12.93  783.49   14.87 1115.24   12.57 1189.06    10.6 1205.28    7.32
 1216.42    3.02 1219.17     .85 1220.27   -1.73 1232.31   -3.03 1239.04    -1.9
 1239.88     .68    1243    4.42 1252.68    9.38 1264.94   11.64 1349.11   12.14
 1479.16   17.35 1507.77   13.26 1626.79   13.79 1747.73   11.78 1891.71   13.88
#Mann= 4 ,-1 , 0
       0     .15       0 1115.24     .06       0 1264.94     .15       0
 1479.16     .99       0
#Block Obstruct= 2 , 0
       0     480      16               0
Bank Sta=1189.06,1264.94
XS Rating Curve= 0
Exp/Cntr=.3,.1

Type RM Length L Ch R = 1 ,3384.195,665.4,676.99,685.32
BEGIN DESCRIPTION:
471v4
Bank Station offset =      4119
END DESCRIPTION:
XS GIS Cut Line= 6
      3232300.49    13804958.477     3231823.465     13804355.24
     3231763.363    13804352.077     3231696.934    13804348.914
     3231621.806    13804344.959     3231406.319    13803797.297
#Sta/Elev= 30
       0   12.46  103.63   12.18  252.82    13.4  367.63    12.7  483.12   13.45
  551.15   12.02  716.37   13.11  741.65   11.72  769.06   11.55  769.77    10.9
  817.31     9.4  846.07    5.55  861.49     .21  862.83    -.94  869.69   -3.03
  874.25   -2.74  881.06   -3.79  889.85   -1.16  890.13      .1  893.68    2.84
  910.89    8.43  921.01     9.8  970.98   11.35  979.22    11.1 1033.54   12.17
 1097.87   11.47 1115.17   13.57 1321.14   11.46 1405.64    12.2 1559.51   11.83
#Mann= 3 ,-1 , 0
       0     .15       0  817.31     .06       0  921.01     .15       0
Bank Sta=817.31,921.01
XS Rating Curve= 0
Exp/Cntr=.3,.1

Type RM Length L Ch R = 1 ,2707.204,550.8,583.64,646.67
BEGIN DESCRIPTION:
471v3
Bank Station offset =      4373
END DESCRIPTION:
XS GIS Cut Line= 6
     3232399.842    13804480.344     3232339.608    13804321.159
     3232256.859    13803956.804     3232077.795    13803871.711
     3231926.001    13803624.608     3231853.405     13803493.03
#Sta/Elev= 30
       0   12.76   89.42   11.94  220.74    11.6  252.29   12.14  394.43   12.05
  514.37   11.13   580.5    9.41  600.67    5.68   612.6    2.21  618.13   -3.76
  621.93   -4.78  626.83   -5.03  643.64   -3.78  651.38    -.94  652.41     .07
  656.79    2.13  667.52    2.23  672.24    4.44   680.2    6.96  691.54    9.24
  702.75   10.29  823.69   11.23  871.08   15.85  889.01   16.95  902.68   16.86
   993.7   12.15 1054.26   11.54 1121.28   12.11 1150.37   13.99 1182.62   11.82
#Mann= 3 ,-1 , 0
       0     .15       0   580.5     .05       0  702.75     .15       0
Bank Sta=580.5,691.54
XS Rating Curve= 0
Exp/Cntr=.3,.1

Type RM Length L Ch R = 1 ,2123.560,92.74,101.57,111.02
BEGIN DESCRIPTION:
Copy of 471s1d:  XS 4/4.
Bank Station offset =      4389
END DESCRIPTION:
XS GIS Cut Line= 6
     3232635.453    13804509.634     3232668.785    13804080.122
     3232666.412    13803831.814     3232675.243    13803713.043
      3232682.85     13803534.27     3232566.838    13803344.087
#Sta/Elev= 30
       0   12.28  116.32   12.38  132.07   11.58  148.39   12.11  229.37   10.73
  303.55   10.09     329   10.67   359.1   10.31  377.03     9.7  434.22     4.4
  477.45    4.84  496.58    9.03  548.78    9.55  567.73     5.3  583.18    3.12
  593.33    -1.1  611.21   -3.89  636.29    -.99  645.41     .49  647.01    1.76
  652.08    1.85  702.24    8.58  746.53    9.79  774.96   11.05  815.97   11.82
  941.27   11.72 1009.44      11 1044.58    12.8 1095.88    13.2 1199.96   12.24
#Mann= 3 ,-1 , 0
       0     .99       0  548.78     .05       0  746.53     .15       0
Bank Sta=548.78,702.24
XS Rating Curve= 0
Exp/Cntr=.5,.3

Type RM Length L Ch R = 1 ,2021.986,89.82,85.5,87.47
BEGIN DESCRIPTION:
XS 3/4. (COPY of 471s1d)
Bank Station offset =      4413
END DESCRIPTION:
XS GIS Cut Line= 6
     3232720.453    13804509.634     3232753.785    13804080.122
     3232751.412    13803831.814     3232760.243    13803713.043
      3232767.85     13803534.27     3232651.838    13803344.087
#Sta/Elev= 30
       0   11.93   78.73   11.54   93.14   10.53  135.34   10.26  181.25   11.25
   208.6    9.81   264.7   10.01  325.96    9.48  337.34   11.37  355.63   11.28
  374.15    9.37  391.57    8.64  404.73    9.14  440.08    8.62  524.57    9.55
  543.52     5.3  558.97    3.12  569.12    -1.1     587   -3.89  612.08    -.99
   621.2     .49   622.8    1.76  627.87    1.85  678.03    8.58  722.32    9.79
  854.79    11.9 1009.44   10.47 1029.26   11.72 1060.14   12.53 1199.96   12.89
#Mann= 3 ,-1 , 0
       0     .15       0  524.57     .05       0  678.03     .15       0
#XS Ineff= 2 , 0
       0     522    12.3     660       0    12.3
Permanent Ineff=
       F       F
Bank Sta=524.57,678.03
XS Rating Curve= 0
Exp/Cntr=.5,.3

Type RM Length L Ch R = 3 ,1979.236,,,
BEGIN DESCRIPTION:
(South) Broadway (Old State Route 146), 471s1
Assumed high chord across bridge 1.5 ft above TOR, based on typical curb height of 0.5 ft.
Assumed low chord 3.2 ft below TOR.
Bridge opening 119.11.
Top of deck/roadway extensions assumed based on aerial photos and GIS tin elevations.
END DESCRIPTION:
Bridge Culvert--1,0,-1,-1, 0
Deck Dist Width WeirC Skew NumUp NumDn MinLoCord MaxHiCord MaxSubmerge Is_Ogee
22.7,40,2.6,0, 10, 10, 12.28, , .95, 0, 0,0,,
       1  476.14  531.12  531.12     591  650.97  650.97  709.12     959    1199
    13.2   12.59    12.3    13.8   13.78    13.8    12.3   12.43    12.8      13
       0       0       0     9.6    9.58     9.6       0       0       0       0
      33  468.14  523.12  523.12     583  642.97  642.97  701.12     951    1232
    13.2   12.59    12.3    13.8   13.78    13.8    12.3   12.43    12.8      13
       0       0       0     9.6    9.58     9.6       0       0       0       0
Pier Skew, UpSta & Num, DnSta & Num=  ,560.34, 4 ,552.81, 4 , 3 , 3 , 0 ,0,
    1.35    1.35     2.5     2.5
   -3.18     6.6     6.6     9.1
    1.35    1.35     2.5     2.5
   -3.18     6.6     6.6     9.1
Pier Skew, UpSta & Num, DnSta & Num=  ,590.7, 4 ,583.17, 4 , 3 , 3 , 0 ,0,
    1.35    1.35     2.5     2.5
   -3.59     6.6     6.6     9.1
    1.35    1.35     2.5     2.5
   -3.59     6.6     6.6     9.1
Pier Skew, UpSta & Num, DnSta & Num=  ,620.81, 4 ,613.28, 4 , 3 , 3 , 0 ,0,
    1.35    1.35     2.5     2.5
    2.31     6.6     6.6     9.1
    1.35    1.35     2.5     2.5
    2.31     6.6     6.6     9.1
BR Coef=-1 , 0 , 0 ,, 0 ,,,.8,0,,0,
WSPro=,,,, 1 ,,,, 0 ,,,, 0 ,,,,-1 ,-1 ,-1 , 0 , 0 , 0 , 0 , 0
BC Design=,, 0 ,, 0 ,,,,,,

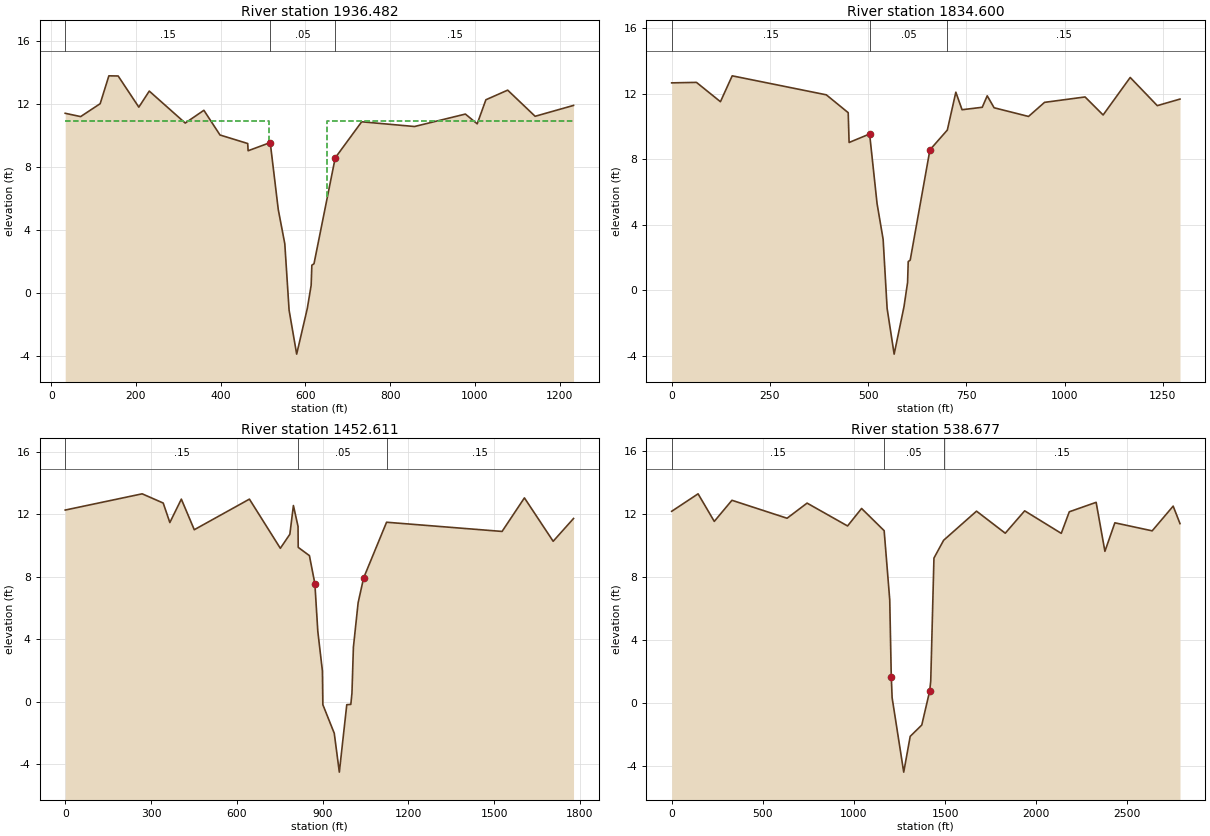
Type RM Length L Ch R = 1 ,1936.482,103.49,101.88,100.55
BEGIN DESCRIPTION:
471s1d:  XS 2/4.
Bank Station offset =      4454
END DESCRIPTION:
XS GIS Cut Line= 6
     3232804.453    13804509.634     3232837.785    13804080.122
     3232835.412    13803831.814     3232844.243    13803713.043
      3232851.85     13803534.27     3232735.838    13803344.087
#Sta/Elev= 30
      33   11.41   69.43    11.2  115.56   12.02  136.09   13.79  157.99   13.78
   206.8    11.8  231.45   12.82  316.34   10.79  360.38    11.6  398.47   10.03
  463.83    9.49  464.78    9.03  516.98    9.55  535.93     5.3  551.38    3.12
  561.53    -1.1  579.41   -3.89  604.49    -.99  613.61     .49  615.21    1.76
  620.28    1.85  670.44    8.58  732.83   10.87  857.58   10.57  977.69   11.36
 1005.59   10.74 1026.09   12.27 1077.52   12.88 1142.31   11.22 1232.96   11.91
#Mann= 3 ,-1 , 0
      33     .15       0  516.98     .05       0  670.44     .15       0
#XS Ineff= 2 , 0
       0     515    10.9     652       0    10.9
Permanent Ineff=
       F       F
Bank Sta=516.98,670.44
XS Rating Curve= 0
Exp/Cntr=.5,.3

Type RM Length L Ch R = 1 ,1834.600,418.42,381.99,351.89
BEGIN DESCRIPTION:
Copy of 471s1d:  XS 1/4.
Bank Station offset =      4434
END DESCRIPTION:
XS GIS Cut Line= 6
     3232904.453    13804509.634     3232937.785    13804080.122
     3232935.412    13803831.814     3232944.243    13803713.043
      3232951.85     13803534.27     3232745.317    13803294.693
#Sta/Elev= 30
       0   12.67   63.07    12.7   124.1   11.52  154.02    13.1  393.51   11.94
  449.22   10.85  451.49    9.03  503.69    9.55  522.64     5.3  538.09    3.12
  548.24    -1.1  566.12   -3.89   591.2    -.99  600.32     .49  601.92    1.76
  606.99    1.85  657.15    8.58  701.44    9.79   723.1    12.1  738.92   11.03
  790.33   11.18  802.95   11.88  820.48   11.15  908.07   10.62   948.8   11.48
 1051.93   11.81 1097.87   10.71 1166.79      13 1235.71   11.28  1293.5   11.68
#Mann= 3 ,-1 , 0
       0     .15       0  503.69     .05       0  701.44     .15       0
Bank Sta=503.69,657.15
XS Rating Curve= 0
Exp/Cntr=.3,.1

Type RM Length L Ch R = 1 ,1452.611,878.23,913.93,954.77
BEGIN DESCRIPTION:
471v2
Bank Station offset =      4042
END DESCRIPTION:
XS GIS Cut Line= 6
     3233765.937    13804424.459     3233486.509    13803989.792
     3233326.169    13803792.702     3233055.475    13803593.545
     3232933.861    13803319.164     3232766.204    13802990.059
#Sta/Elev= 30
       0   12.28  269.14   13.32  342.66   12.73  365.87   11.48  406.08   12.98
  451.32   11.02   644.1   12.98  752.23    9.83  785.49   10.73  797.93   12.57
   814.1   11.23  814.74    9.89  853.91    9.36  872.92    7.57  883.26    4.51
  899.36    1.97  900.88    -.19  940.77   -2.02   958.5   -4.51  984.51    -.19
  998.65    -.17 1002.62     .55 1007.69    3.49 1024.18    6.34 1043.42    7.93
 1123.66    11.5  1527.5   10.91 1605.69   13.06 1706.18   10.28 1777.38   11.74
#Mann= 3 ,-1 , 0
       0     .15       0  814.74     .05       0 1123.66     .15       0
Bank Sta=872.92,1043.42
XS Rating Curve= 0
Exp/Cntr=.3,.1

Type RM Length L Ch R = 1 ,538.677 ,471.37,538.68,673.17
BEGIN DESCRIPTION:
471v1
Bank Station offset =      3727
END DESCRIPTION:
XS GIS Cut Line= 6
     3234318.584    13804418.249     3234039.156    13803437.145
     3233983.477    13803337.032     3233437.827     13802637.86
     3233371.312    13802585.598      3232946.28    13802052.422
#Sta/Elev= 30
       0    12.2  144.92   13.31  233.74   11.56  330.63    12.9  633.03   11.76
  742.86   12.72   964.9   11.27 1041.84   12.38 1165.68   10.97 1196.29    6.58
  1204.7    1.71 1209.42     .36 1273.04   -4.36 1308.52   -2.09 1372.02   -1.37
 1415.04     .77 1421.22    1.42 1438.84    9.23 1491.84   10.36 1672.39   12.21
 1830.06   10.81 1936.55   12.23 2137.31    10.8 2181.37   12.17 2328.61   12.77
 2376.73    9.66  2431.3   11.47 2636.06   10.96 2751.16   12.53 2788.65   11.42
#Mann= 3 ,-1 , 0
       0     .15       0 1165.68     .05       0 1491.84     .15       0
Bank Sta=1204.7,1415.04
XS Rating Curve= 0
Exp/Cntr=.3,.1

Chan Stop Cuts=-1